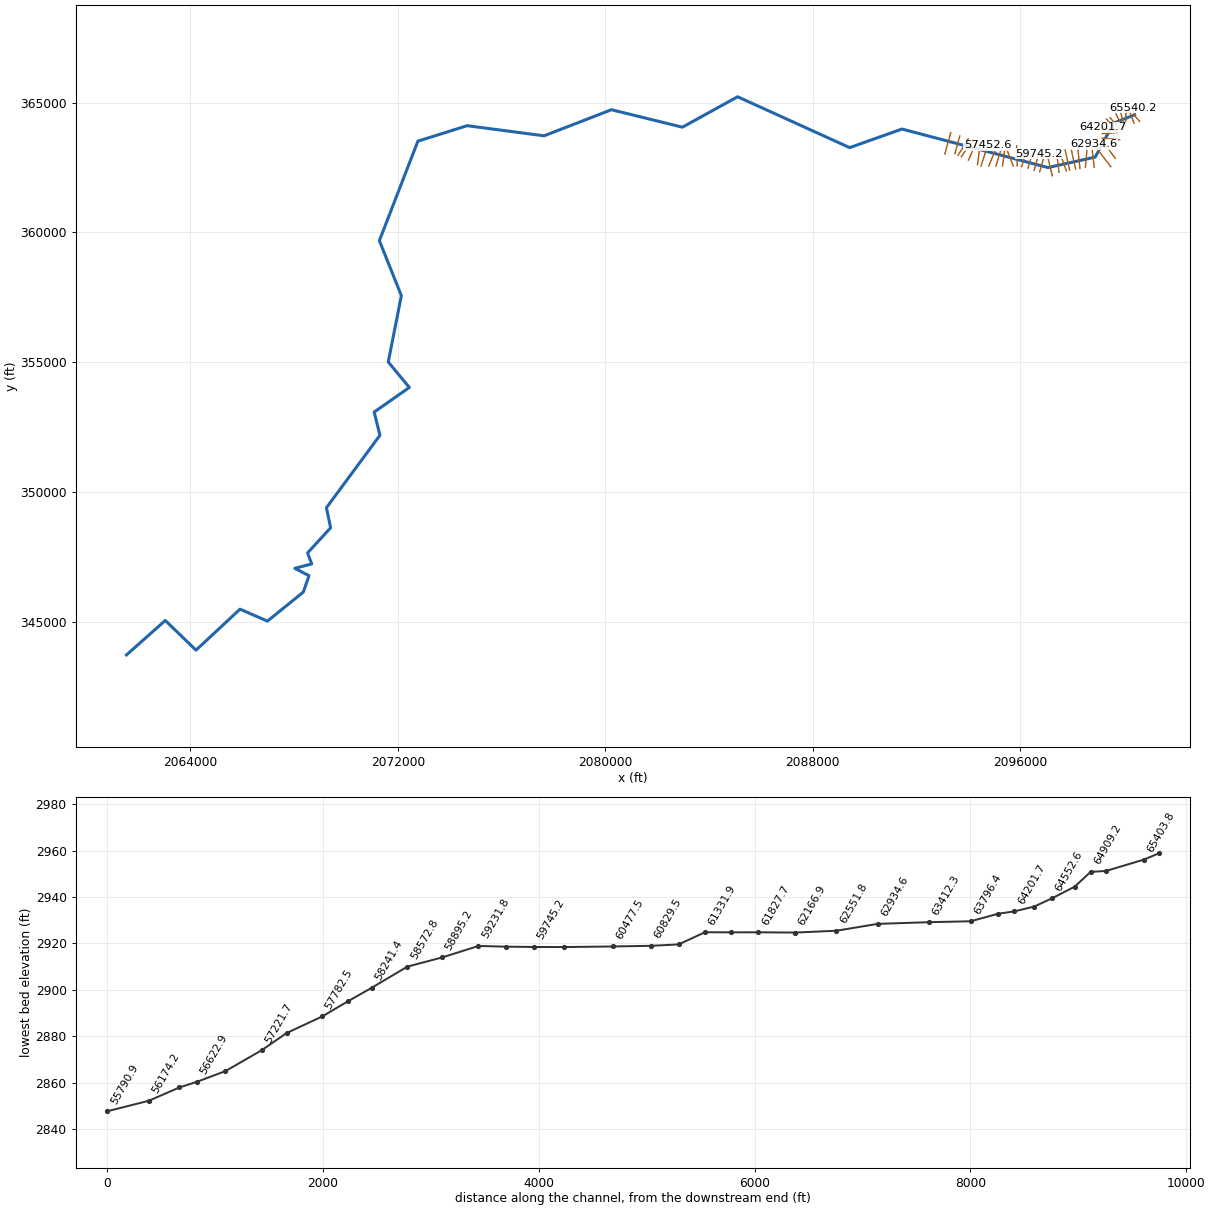
--- LittleClCk.prj (project) ---

Proj Title=LittleClCk
Current Plan=p01
Default Exp/Contr=0,0
English Units
Geom File=g01
Flow File=f01
Plan File=p01
BEGIN DESCRIPTION:
END DESCRIPTION:
DSS Export Rating Curves= 0
DSS Export Rating Curve Sorted= 0
DSS Export Volume Flow Curves= 0
DXF OffsetX= 0
DXF OffsetY= 0
DXF ScaleX= 0
DXF ScaleY= 0

--- LittleClCk.p01 (plan) ---

Plan Title=Floodplain
Program Version=4.00
Geom File=g01
Flow File=f01
K Sum by GR=0
Std Step Tol=0.01
Critical Tol=0.01
Num of Std Step Trials=20
Max Error Tol=0.3
Flow Tol Ratio=0.001
Split Flow NTrial=30
Split Flow Tol=0.02
Split Flow Ratio=0.02
Log Output Level=0
Friction Slope Method=1
Unsteady Friction Slope Method=2
Unsteady Bridges Friction Slope Method=1
Global Log Level=0
CheckData=False
Run HTab=0
Run UNet=0
Run PostProcess=0
UNET Theta=0
UNET Theta Warmup=0
UNET ZTol=0
UNET ZSATol=0
UNET MxIter=0
UNET MaxInSteps=0
UNET DtIC=0
UNET DtMin=0
UNET MaxCRTS=0
UNET WFStab=0
UNET SFStab=0
UNET WFX=0
UNET SFX=0
UNET DSS MLevel=0
UNET DZMax Abort=0
UNET Convert EG Bridges=0
UNET Use Existing IB Tables=0
UNET Froude Limit=0
UNET Froude Power=0
Write IC File=0
Echo Input=False
Echo Output=False
Write Detailed=0

--- LittleClCk.f01 (steady flow) ---

Flow Title=NFF Regression Equation
Program Version=4.00
Number of Profiles=1
Profile Names=P100yr
River Rch & RM=LittleClCk,Main      ,65540.2
545.8678
River Rch & RM=LittleClCk,Main      ,63412.3
594.3168
River Rch & RM=LittleClCk,Main      ,62166.9
659.3741
River Rch & RM=LittleClCk,Main      ,58895.2
726.6639
River Rch & RM=LittleClCk,Main      ,58572.8
822.0363
River Rch & RM=LittleClCk,Main      ,55456.8
909.3278
River Rch & RM=LittleClCk,Main      ,55152.7
1356.993
River Rch & RM=LittleClCk,Main      ,51073.5
1502.968
River Rch & RM=LittleClCk,Main      ,50759.4
2221.530
River Rch & RM=LittleClCk,Main      ,45953.4
2441.562
River Rch & RM=LittleClCk,Main      ,42872
2600.258
River Rch & RM=LittleClCk,Main      ,36722.8
2794.616
River Rch & RM=LittleClCk,Main      ,25797
3099.865
River Rch & RM=LittleClCk,Main      ,20933.4
3435.177
River Rch & RM=LittleClCk,Main      ,11128.6
3792.681
River Rch & RM=LittleClCk,Main      ,8987.1
4690.123
River Rch & RM=LittleClCk,Main      ,3964.7
4821.964
Boundary for River Rch & Prof#=LittleClCk,Main      ,1
Up Type=0
Dn Type=3
Dn Slope=0.000174

--- LittleClCk.g01 (geometry) ---

Geom Title=USGS 10m DEM
Program Version=4.10

River Reach=LittleClCk      ,Main
Reach XY= 30
     2100406.215      364530.025     2099603.273      364217.464
     2098887.165      362902.932     2097067.958      362498.998
      2091437.69      363983.727     2089418.652      363267.968
     2085097.255      365227.359     2082969.828      364055.396
     2080233.725      364728.098      2077634.34      363722.825
     2074668.874      364112.833     2072769.781       363517.28
     2071283.731      359684.021     2072131.882      357565.961
     2071626.333      355007.965      2072439.47      354027.814
     2071083.265       353078.63     2071305.779      352184.391
     2069242.733      349393.629     2069403.364      348620.709
     2068515.167      347651.252      2068674.63      347227.727
     2068023.824      347057.861     2068571.861      346774.394
     2068348.867      346141.318     2066967.437      345024.457
      2065910.51      345484.816     2064213.326      343905.321
     2063028.151      345048.663     2061530.687      343720.972

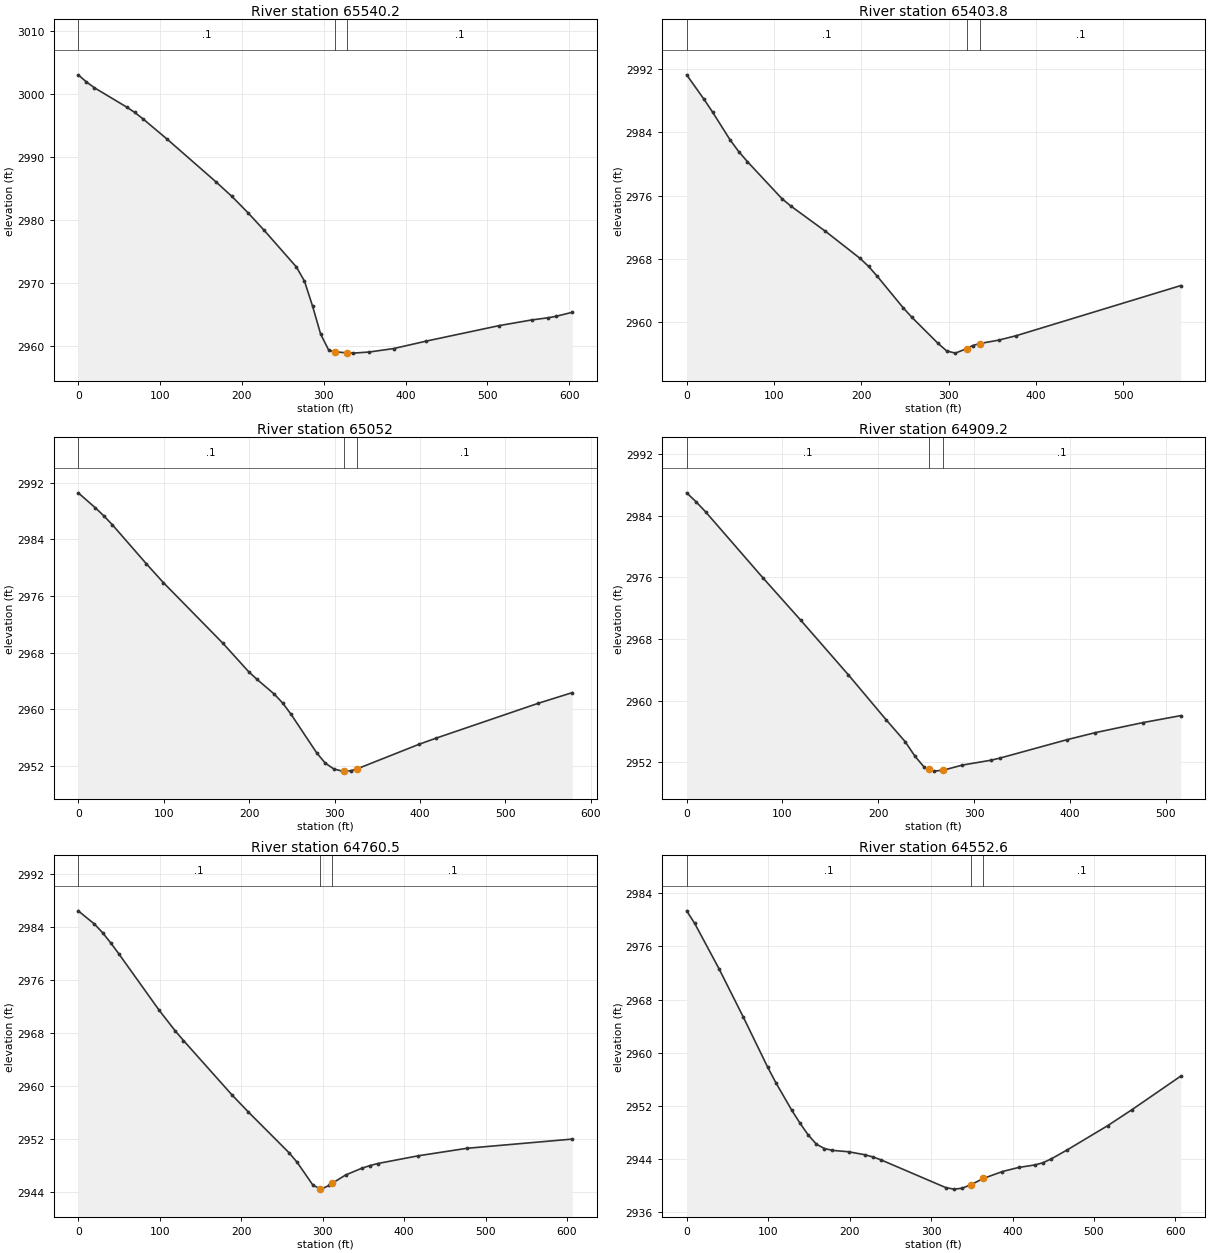
Type RM Length L Ch R = 1 ,65540.2 ,152.9,136.4,139
XS GIS Cut Line= 3
     2100595.821      364280.654     2100409.333      364497.967
     2100339.978      364807.753
#Sta/Elev= 27
       0 3003.08     9.9 3001.96    19.8 3001.02    59.2 2997.95    69.1 2997.09
      79 2996.09   108.6 2992.85   167.9  2986.1   187.6 2983.76   207.4 2981.14
   227.1 2978.36   266.6 2972.51   276.5 2970.25   286.4 2966.27   296.3 2961.81
   306.2 2959.25   313.4 2959.02   328.4 2958.84     336  2958.8   355.8 2958.98
   385.6 2959.53   425.2 2960.71   514.5 2963.18   554.2 2964.08     574 2964.42
     584 2964.66   603.8  2965.3
#Mann= 3 , 0 , 0
       0      .1       0   313.4    .045       0   328.4      .1       0
Bank Sta=313.4,328.4
XS Rating Curve= 0 ,0
Exp/Cntr=0.3,0.1

Type RM Length L Ch R = 1 ,65403.8 ,355.8,351.3,344.1
XS GIS Cut Line= 2
     2100380.807      364209.438     2100188.852      364741.852
#Sta/Elev= 23
       0 2991.24    19.9 2988.15    29.8 2986.52    49.6 2983.06    59.6 2981.56
    69.5  2980.3   109.2 2975.61   119.2  2974.7   158.9 2971.51   198.6 2968.09
   208.5 2967.06   218.4 2965.82   248.2 2961.83   258.2 2960.63     288 2957.36
   297.9 2956.41   307.8 2956.13   320.9  2956.7   327.7 2957.09   335.9 2957.34
   357.4 2957.77   377.3 2958.32     566 2964.65
#Mann= 3 , 0 , 0
       0      .1       0   320.9    .045       0   335.9      .1       0
Bank Sta=320.9,335.9
XS Rating Curve= 0 ,0
Exp/Cntr=0.3,0.1

Type RM Length L Ch R = 1 ,65052   ,134.9,142.7,150.5
XS GIS Cut Line= 2
     2100065.502      364111.001     2100076.875      364689.157
#Sta/Elev= 23
       0 2990.59    19.9 2988.49    29.9 2987.34    39.9 2986.08    79.8 2980.55
    99.7 2977.89   169.5  2969.3   199.4 2965.31   209.4  2964.2   229.3 2962.15
   239.3 2960.87   249.2 2959.26   279.2 2953.81   289.1 2952.38   299.1 2951.55
   309.1 2951.24   311.2 2951.25     319  2951.3   326.2 2951.55   398.8 2955.03
   418.8  2955.9   538.4 2960.83   578.3 2962.34
#Mann= 3 , 0 , 0
       0      .1       0   311.2    .045       0   326.2      .1       0
Bank Sta=311.2,326.2
XS Rating Curve= 0 ,0
Exp/Cntr=0.3,0.1

Type RM Length L Ch R = 1 ,64909.2 ,145.2,148.3,151.3
XS GIS Cut Line= 2
     2100026.202      364116.629     2099866.999      364606.991
#Sta/Elev= 20
       0 2986.95     9.9 2985.78    19.8 2984.48    79.3 2975.96     119 2970.43
   168.6 2963.36   208.2  2957.5     228 2954.67     238 2952.82   247.9 2951.35
   252.8  2951.1   257.8 2950.84   267.8 2950.96   287.5 2951.62   317.3 2952.25
   327.2 2952.54   396.6 2954.91   426.3 2955.83   475.9 2957.13   515.6 2958.04
#Mann= 3 , 0 , 0
       0      .1       0   252.8    .045       0   267.8      .1       0
Bank Sta=252.8,267.8
XS Rating Curve= 0 ,0
Exp/Cntr=0.3,0.1

Type RM Length L Ch R = 1 ,64760.5 ,201.7,207.9,214.2
XS GIS Cut Line= 2
     2099948.693      364022.752     2099687.117      364569.898
#Sta/Elev= 24
       0 2986.49    19.9 2984.49    29.8  2983.2    39.8 2981.66    49.7 2980.02
    99.4 2971.46   119.3 2968.32   129.2  2966.9   188.9 2958.66   208.8 2956.11
   258.5 2949.98   268.4 2948.56   288.3 2945.02   296.8 2944.54   298.3 2944.45
   308.2 2945.03   311.8 2945.33   328.1 2946.58     348  2947.6   357.9    2948
   367.8 2948.32   417.6 2949.49   477.2 2950.62   606.5 2952.01
#Mann= 3 , 0 , 0
       0      .1       0   296.8    .045       0   311.8      .1       0
Bank Sta=296.8,311.8
XS Rating Curve= 0 ,0
Exp/Cntr=0.3,0.1

Type RM Length L Ch R = 1 ,64552.6 ,165,165.3,165.7
XS GIS Cut Line= 2
     2099861.209        363961.9     2099463.055      364419.353
#Sta/Elev= 30
       0 2981.36     9.9 2979.46    39.8 2972.63    69.6 2965.36    99.4 2957.86
   109.4 2955.53   129.2 2951.33   139.2 2949.41   149.1 2947.67   159.1 2946.28
     169 2945.61     179 2945.33   198.8 2945.12   218.7 2944.67   228.7 2944.34
   238.6  2943.9   318.1 2939.73   328.1  2939.5     338 2939.63   349.1 2940.17
   364.1  2941.1   387.7 2942.15   407.6 2942.76   427.5 2943.14   437.4 2943.47
   447.4 2944.04   467.3 2945.41     517 2949.06   546.8 2951.46   606.5  2956.5
#Mann= 3 , 0 , 0
       0      .1       0   349.1    .045       0   364.1      .1       0
Bank Sta=349.1,364.1
XS Rating Curve= 0 ,0
Exp/Cntr=0.3,0.1

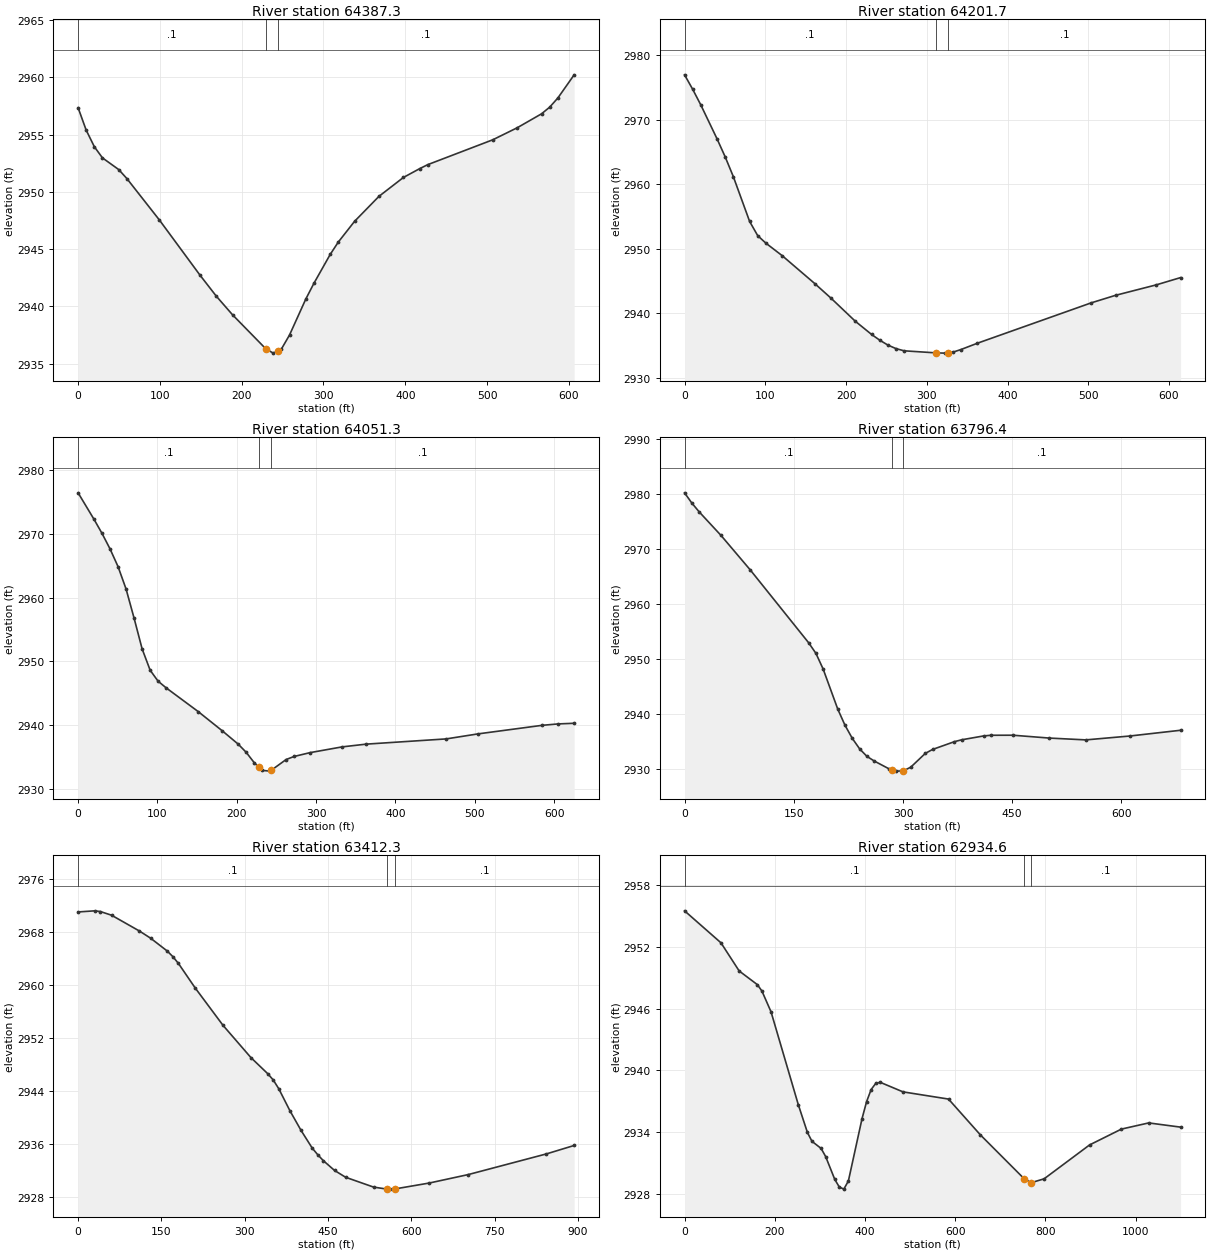
Type RM Length L Ch R = 1 ,64387.3 ,177.9,185.5,199.6
XS GIS Cut Line= 2
     2099715.806      363912.201     2099317.652      364369.654
#Sta/Elev= 30
       0 2957.34     9.9 2955.38    19.9 2953.93    29.8 2952.96    49.7 2951.94
    59.6 2951.16    99.4 2947.54   149.1 2942.72     169 2940.89   188.9 2939.26
   229.6 2936.29   238.6 2935.92   244.6 2936.14   248.6 2936.28   258.5  2937.5
   278.4 2940.64   288.3 2942.01   308.2 2944.53   318.1 2945.61     338 2947.42
   367.8  2949.6   397.7 2951.25   417.6 2952.02   427.5 2952.37     507 2954.54
   536.9 2955.59   566.7 2956.81   576.6 2957.39   586.6 2958.19   606.5 2960.21
#Mann= 3 , 0 , 0
       0      .1       0   229.6    .045       0   244.6      .1       0
Bank Sta=229.6,244.6
XS Rating Curve= 0 ,0
Exp/Cntr=0.3,0.1

Type RM Length L Ch R = 1 ,64201.7 ,134.6,150.3,159.2
XS GIS Cut Line= 2
     2099782.072      363872.843     2099193.943       364050.51
#Sta/Elev= 28
       0 2976.97    10.1 2974.72    20.1 2972.31    40.3 2967.03    50.4 2964.23
    60.4 2961.19    80.6 2954.24    90.6 2952.04   100.7 2950.88   120.9 2948.94
   161.2 2944.62   181.3 2942.36   211.5 2938.77   231.6 2936.73   241.7 2935.84
   251.8 2935.08   261.9 2934.53   271.9 2934.19   311.3 2933.87   322.3 2933.83
   326.3 2933.89   332.4 2933.98   342.4 2934.39   362.6 2935.36   503.6 2941.62
   533.8 2942.79   584.2 2944.41   614.4 2945.54
#Mann= 3 , 0 , 0
       0      .1       0   311.3    .045       0   326.3      .1       0
Bank Sta=311.3,326.3
XS Rating Curve= 0 ,0
Exp/Cntr=0.3,0.1

Type RM Length L Ch R = 1 ,64051.3 ,258.4,254.5,250.6
XS GIS Cut Line= 2
     2099785.232      363853.333     2099161.851      363805.356
#Sta/Elev= 30
       0 2976.42    20.2 2972.24    30.2 2970.05    40.3 2967.62    50.4 2964.84
    60.5 2961.33    70.6 2956.76    80.7 2951.96    90.8 2948.62   100.8  2946.9
   110.9 2945.86   151.3 2942.14   181.5 2939.14   201.7 2937.04   211.8 2935.76
   221.8 2934.15   228.1 2933.38   231.9 2932.92     242  2932.8   243.1  2932.9
   262.2 2934.62   272.3  2935.1   292.4  2935.7   332.8  2936.6     363 2937.03
   463.9 2937.85   504.2 2938.64   584.9 2939.98   605.1  2940.2   625.2  2940.3
#Mann= 3 , 0 , 0
       0      .1       0   228.1    .045       0   243.1      .1       0
Bank Sta=228.1,243.1
XS Rating Curve= 0 ,0
Exp/Cntr=0.3,0.1

Type RM Length L Ch R = 1 ,63796.4 ,402.7,384.1,365.4
XS GIS Cut Line= 2
     2099831.206      363569.492     2099153.232      363636.809
#Sta/Elev= 30
       0 2980.16      10  2978.3      20 2976.71    50.1 2972.41    90.2 2966.15
   170.3 2952.92   180.4 2950.98   190.4  2948.1   210.4 2940.84   220.4 2937.89
   230.4 2935.51   240.5  2933.6   250.5 2932.24   260.5  2931.4   280.5    2930
   285.1  2929.8   290.6 2929.56   300.1  2929.6   310.6 2930.27   330.6 2932.78
   340.6  2933.5   370.7 2934.92   380.7 2935.26   410.8 2935.96   420.8 2936.08
   450.9 2936.09     501 2935.57   551.1 2935.24   611.2 2935.94   681.3 2936.99
#Mann= 3 , 0 , 0
       0      .1       0   285.1    .045       0   300.1      .1       0
Bank Sta=285.1,300.1
XS Rating Curve= 0 ,0
Exp/Cntr=0.3,0.1

Type RM Length L Ch R = 1 ,63412.3 ,487.8,477.7,466.5
XS GIS Cut Line= 2
     2099660.159      362851.026      2099139.01      363576.739
#Sta/Elev= 30
       0 2971.07    30.1 2971.24    40.2 2971.13    60.2 2970.58   110.4 2968.19
   130.5 2967.11   160.6 2965.16   170.7 2964.31   180.7 2963.29   210.8 2959.59
     261 2953.93   311.2 2949.06   341.3 2946.64   351.4 2945.68   361.4 2944.35
   381.5 2941.02   401.6 2938.04   421.6 2935.38   431.7 2934.36   441.7 2933.47
   461.8    2932   481.9 2930.96   532.1 2929.48   555.6 2929.18   562.2 2929.17
   570.6  2929.2   632.4 2930.09   702.7 2931.37   843.3 2934.49   893.4 2935.77
#Mann= 3 , 0 , 0
       0      .1       0   555.6    .045       0   570.6      .1       0
Bank Sta=555.6,570.6
XS Rating Curve= 0 ,0
Exp/Cntr=0.3,0.1

Type RM Length L Ch R = 1 ,62934.6 ,387.8,382.7,374.2
XS GIS Cut Line= 2
     2099489.733      362529.996     2098822.461      363404.198
#Sta/Elev= 30
       0 2955.51    80.7  2952.4   121.1 2949.66   161.4 2948.33   171.5 2947.71
   191.7 2945.69   252.2 2936.65   272.4 2933.95   282.5 2933.09   302.7  2932.4
   312.8 2931.61     333 2929.39     343 2928.65   353.1 2928.44   363.2 2929.23
   393.5  2935.3   403.6 2936.95   413.7 2938.13   423.8 2938.72   433.8 2938.83
   484.3  2937.9   585.2  2937.2   655.8 2933.72   753.6 2929.42   768.6 2929.07
   797.1 2929.44     898 2932.74   968.6 2934.28  1029.1 2934.88  1099.8 2934.47
#Mann= 3 , 0 , 0
       0      .1       0   753.6    .045       0   768.6      .1       0
#XS Ineff= 2 , 0
          440.88 2938.68
Permanent Ineff=
       F       F
Bank Sta=753.6,768.6
XS Rating Curve= 0 ,0
Exp/Cntr=0.3,0.1

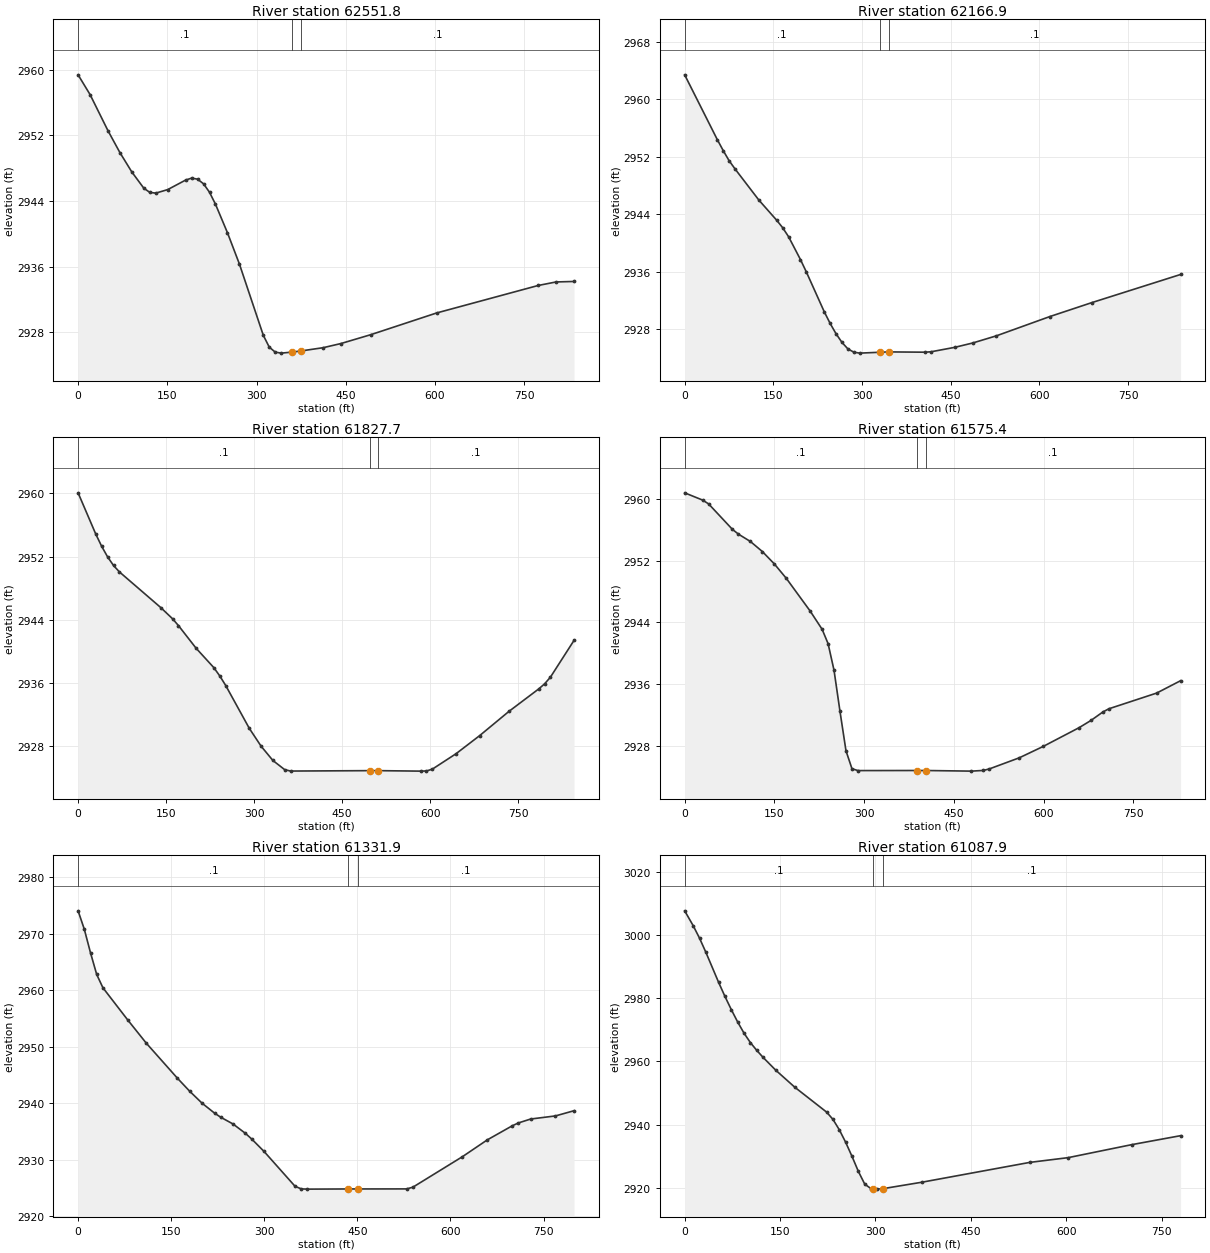
Type RM Length L Ch R = 1 ,62551.8 ,387.7,384.9,381.8
XS GIS Cut Line= 2
     2098847.421       362503.64     2098757.069      363332.503
#Sta/Elev= 30
       0 2959.38    20.1 2956.98    50.2 2952.58    70.3 2949.91    90.4 2947.54
   110.5 2945.57   120.6 2945.06   130.6 2944.97   150.7  2945.4   180.8 2946.56
   190.9  2946.8   200.9 2946.67     211  2946.1     221 2945.07     231 2943.62
   251.1 2940.15   271.2 2936.34   311.4 2927.65   321.4 2926.21   331.5  2925.6
   341.6 2925.48   359.2  2925.6   374.2 2925.74   411.9 2926.14     442 2926.65
   492.2 2927.73   602.7 2930.37   773.5 2933.72   803.6 2934.15   833.8 2934.21
#Mann= 3 , 0 , 0
       0      .1       0   359.2    .045       0   374.2      .1       0
Bank Sta=359.2,374.2
XS Rating Curve= 0 ,0
Exp/Cntr=0.3,0.1

Type RM Length L Ch R = 1 ,62166.9 ,333.9,338,342.4
XS GIS Cut Line= 3
     2098509.417      362509.996     2098509.852      362514.881
     2098583.828      363345.366
#Sta/Elev= 28
       0 2963.39    55.1 2954.39    65.2 2952.85    75.2 2951.44    85.3 2950.29
   125.4 2945.98   155.6 2943.17   165.6 2942.14   175.7 2940.88   195.8  2937.7
   205.8 2935.97     236 2930.45     246 2928.82     256 2927.38   266.1 2926.17
   276.1 2925.27   286.2 2924.82   296.2 2924.69   329.9 2924.81   344.9 2924.86
   406.7 2924.82   416.8 2924.88     457  2925.5   487.1  2926.1   527.3  2927.1
   617.7 2929.78     688  2931.7   838.7 2935.63
#Mann= 3 , 0 , 0
       0      .1       0   329.9    .045       0   344.9      .1       0
Bank Sta=329.9,344.9
XS Rating Curve= 0 ,0
Exp/Cntr=0.3,0.1

Type RM Length L Ch R = 1 ,61827.7 ,249.9,252.3,254.4
XS GIS Cut Line= 2
     2098298.663      362470.856     2098207.069      363311.109
#Sta/Elev= 30
       0 2960.08    30.2 2954.84    40.2  2953.3    50.3 2951.96    60.4 2950.87
    70.4 2950.06   140.9 2945.54     161 2944.12   171.1 2943.25   201.2 2940.38
   231.4 2937.92   241.5 2936.87   251.6 2935.66   291.8 2930.23   311.9 2927.97
     332 2926.16   352.2 2924.99   362.2 2924.82   496.9 2924.87   511.9 2924.87
   583.6 2924.81   593.7 2924.83   603.7 2925.06     644 2927.01   684.2  2929.3
   734.6  2932.4   784.9 2935.22   794.9 2935.86     805 2936.72   845.2 2941.38
#Mann= 3 , 0 , 0
       0      .1       0   496.9    .045       0   511.9      .1       0
Bank Sta=496.9,511.9
XS Rating Curve= 0 ,0
Exp/Cntr=0.3,0.1

Type RM Length L Ch R = 1 ,61575.4 ,243.5,243.5,243.5
XS GIS Cut Line= 2
     2098131.332       362439.78     2097952.878      363249.494
#Sta/Elev= 30
       0 2960.76      30 2959.82      40 2959.33    79.9 2956.03    89.9 2955.42
   109.9 2954.47   129.9 2953.17   149.8 2951.58   169.8 2949.72   209.8 2945.48
   229.8 2943.12   239.8 2941.26   249.7 2937.83   259.7  2932.5   269.7 2927.42
   279.7  2925.1   289.7 2924.86   387.9 2924.87   402.9 2924.87   479.5 2924.79
   499.5 2924.88   509.5 2925.08   559.4 2926.51   599.4 2927.98   659.3  2930.4
   679.3 2931.34   699.3 2932.44   709.3 2932.85   789.2 2934.88   829.2 2936.48
#Mann= 3 , 0 , 0
       0      .1       0   387.9    .045       0   402.9      .1       0
Bank Sta=387.9,402.9
XS Rating Curve= 0 ,0
Exp/Cntr=0.3,0.1

Type RM Length L Ch R = 1 ,61331.9 ,243.1,244,244.5
XS GIS Cut Line= 2
      2097902.47      362397.277     2097727.979      363177.135
#Sta/Elev= 30
       0 2974.07      10 2970.82      20 2966.65      30 2962.81      40 2960.46
    79.9 2954.78   109.9 2950.66   159.8 2944.49   179.8 2942.16   199.8 2940.04
   219.8 2938.29   229.8 2937.56   249.7 2936.36   269.7  2934.7   279.7 2933.71
   299.7  2931.5   349.6 2925.34   359.6 2924.88   369.6 2924.84   435.7 2924.87
   450.7 2924.87   529.4 2924.88   539.4 2925.18   619.3 2930.58   659.3 2933.55
   699.2 2936.02   709.2 2936.54   729.2 2937.24   769.2 2937.79   799.1 2938.71
#Mann= 3 , 0 , 0
       0      .1       0   435.7    .045       0   450.7      .1       0
Bank Sta=435.7,450.7
XS Rating Curve= 0 ,0
Exp/Cntr=0.3,0.1

Type RM Length L Ch R = 1 ,61087.9 ,263.5,258.5,269.9
XS GIS Cut Line= 4
      2097775.13      362373.628     2097770.567      362386.202
     2097511.506       363100.02     2097509.079      363106.706
#Sta/Elev= 30
       0 3007.68    13.4 3002.97    23.4 2999.01    33.4 2994.52    53.3 2985.07
    63.3  2980.6    73.3 2976.42    83.3  2972.5    93.3 2968.96   103.3 2965.98
   113.3 2963.52   123.3 2961.29   143.3 2957.22   173.2 2951.84   223.2 2943.97
   233.2 2941.66   243.2 2938.37   253.2  2934.4   263.2 2929.93   273.2 2925.17
   283.2 2921.16   293.2 2919.72   296.3 2919.68   303.1 2919.59   311.3 2919.72
   373.1 2921.78   542.9 2928.06   602.9 2929.55   702.8 2933.66   779.9 2936.51
#Mann= 3 , 0 , 0
       0      .1       0   296.3    .045       0   311.3      .1       0
Bank Sta=296.3,311.3
XS Rating Curve= 0 ,0
Exp/Cntr=0.3,0.1

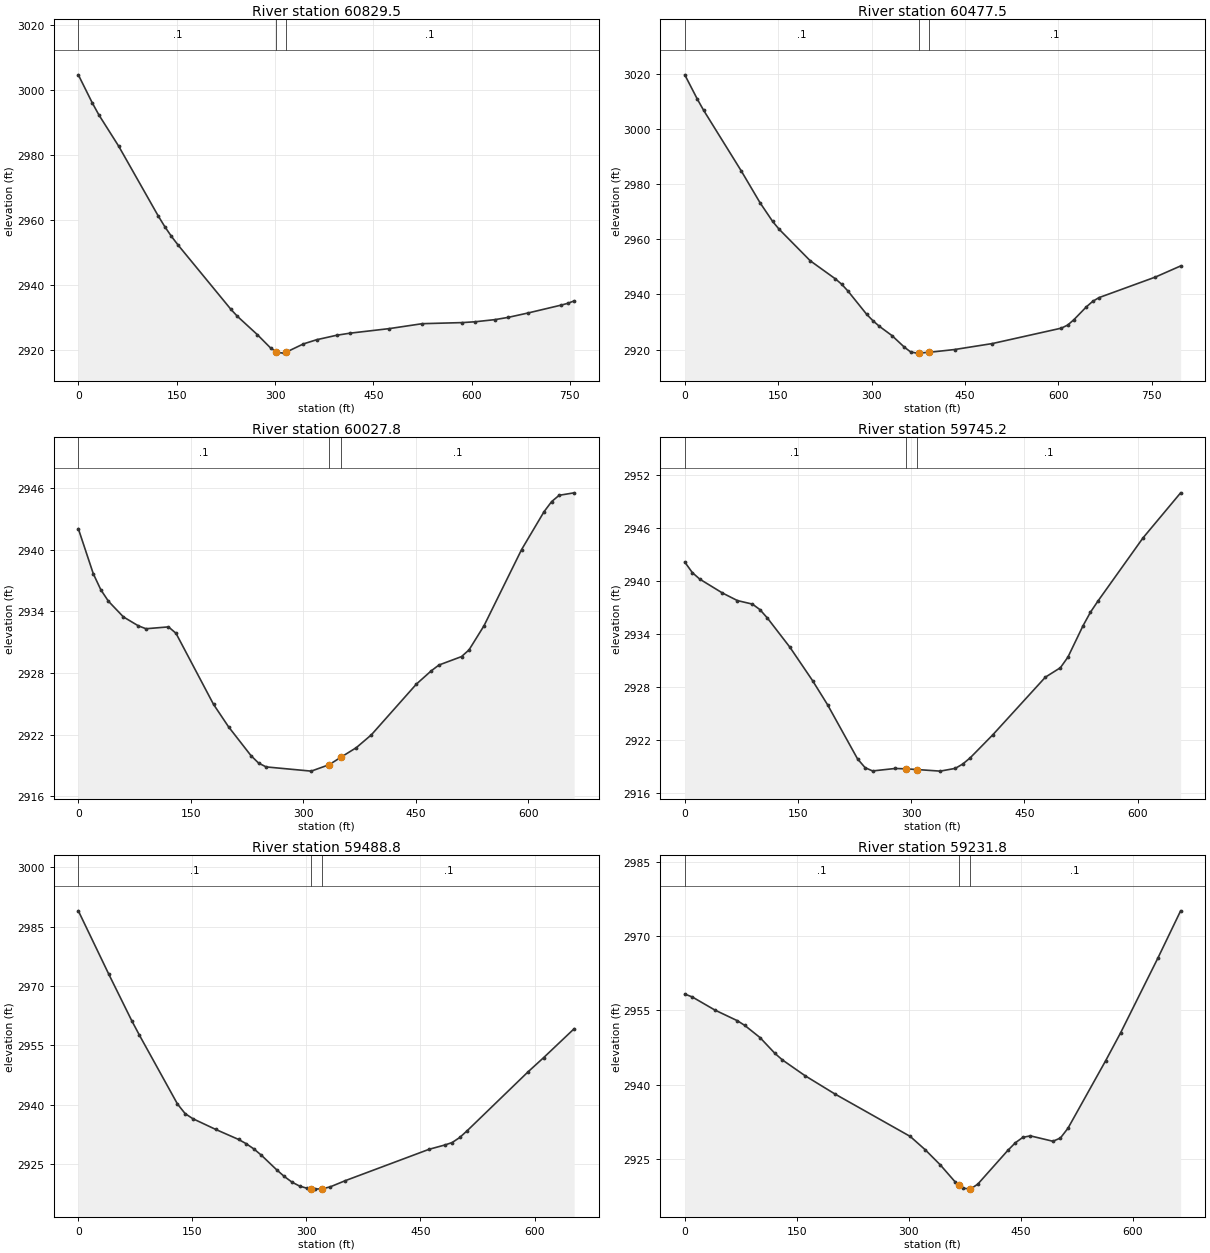
Type RM Length L Ch R = 1 ,60829.5 ,346.7,351.9,357.1
XS GIS Cut Line= 3
     2097491.285      362320.914     2097491.146      362322.061
     2097400.911      363071.905
#Sta/Elev= 30
       0 3004.78    21.3 2996.12    31.4 2992.41    61.6 2982.77     122 2961.23
   132.1 2957.91   142.1 2954.96   152.2  2952.3   232.8 2932.47   242.8  2930.3
     273  2924.7   293.2 2920.59   302.2 2919.35   303.3  2919.2   313.3 2918.98
   317.2 2919.29   343.5 2921.83   363.7 2923.12   393.9 2924.48     414 2925.12
   474.4 2926.54   524.8 2928.06   585.2 2928.39   605.4 2928.65   635.6 2929.31
   655.7    2930   685.9 2931.35   736.3 2933.77   746.3 2934.31   756.4 2935.08
#Mann= 3 , 0 , 0
       0      .1       0   302.2    .045       0   317.2      .1       0
Bank Sta=302.2,317.2
XS Rating Curve= 0 ,0
Exp/Cntr=0.3,0.1

Type RM Length L Ch R = 1 ,60477.5 ,454.4,449.7,441.2
XS GIS Cut Line= 2
     2097233.066      362183.119     2097043.608      362956.946
#Sta/Elev= 30
       0  3019.7    20.2 3010.85    30.2 3006.85    90.8  2984.8     121 2973.24
   141.2 2966.48   151.3 2963.73   201.7 2952.19     242 2945.65   252.1  2943.7
   262.2 2941.22   292.4 2932.74   302.5 2930.42   312.6 2928.44   332.8 2925.08
     353 2920.82     363 2919.12   373.1  2918.7   376.7 2918.75   391.7 2918.97
   433.6 2920.01   494.1 2922.17   605.1 2927.77   615.2 2928.88   625.2 2930.83
   645.4 2935.53   655.5  2937.5   665.6 2938.85   756.3 2946.32   796.7 2950.34
#Mann= 3 , 0 , 0
       0      .1       0   376.7    .045       0   391.7      .1       0
Bank Sta=376.7,391.7
XS Rating Curve= 0 ,0
Exp/Cntr=0.3,0.1

Type RM Length L Ch R = 1 ,60027.8 ,283.9,282.5,280.2
XS GIS Cut Line= 2
     2096744.461      362334.354      2096929.19      362969.136
#Sta/Elev= 30
       0 2942.03      20 2937.64      30 2936.09    40.1 2934.98    60.1 2933.45
    80.1 2932.58    90.2  2932.3   120.2 2932.48   130.2 2931.86   180.3 2924.94
   200.3 2922.76   230.4 2919.94   240.4 2919.23   250.4 2918.86   310.5 2918.45
   334.6 2919.08   349.6 2919.78   370.6 2920.73   390.7 2921.98   450.8 2926.92
   470.8 2928.22   480.8 2928.77   510.9 2929.59   520.9 2930.24   540.9 2932.59
     591    2940     621 2943.69   631.1 2944.67   641.1 2945.28   661.1 2945.52
#Mann= 3 , 0 , 0
       0      .1       0   334.6    .045       0   349.6      .1       0
Bank Sta=334.6,349.6
XS Rating Curve= 0 ,0
Exp/Cntr=0.3,0.1

Type RM Length L Ch R = 1 ,59745.2 ,284.4,256.4,284.8
XS GIS Cut Line= 2
     2096533.112      362399.772     2096716.657      363030.486
#Sta/Elev= 30
       0 2942.11      10 2940.92    19.9 2940.18    49.8 2938.62    69.7 2937.76
    89.6 2937.36    99.5 2936.74   109.5 2935.78   139.3 2932.48   169.2 2928.72
   189.1 2925.99   228.9 2919.86   238.9 2918.87   248.8  2918.5   278.7 2918.78
   292.6 2918.74   307.6 2918.66   338.4 2918.48   358.3 2918.79   368.2 2919.28
   378.2 2919.99   408.1 2922.59   477.7  2929.1   497.6 2930.17   507.6 2931.37
   527.5  2934.9   537.4 2936.44   547.4 2937.71   607.1 2944.85   656.9 2949.94
#Mann= 3 , 0 , 0
       0      .1       0   292.6    .045       0   307.6      .1       0
Bank Sta=292.6,307.6
XS Rating Curve= 0 ,0
Exp/Cntr=0.3,0.1

Type RM Length L Ch R = 1 ,59488.8 ,256.9,257,257
XS GIS Cut Line= 2
      2096296.33      362473.061     2096478.549      363099.218
#Sta/Elev= 30
       0 2989.02    40.1 2972.97    70.2 2961.25    80.3 2957.58   130.4 2940.15
   140.5 2937.72   150.5 2936.45   180.6 2933.73   210.7 2931.19   220.7 2930.12
   230.8  2928.8   240.8 2927.19   260.8 2923.52   270.9 2921.82   280.9  2920.4
     291 2919.39     301 2918.83     306 2918.72     311 2918.62     321 2918.72
   331.1 2919.18   351.2 2920.77   461.5 2928.71   481.6 2929.76   491.6  2930.4
   501.6 2931.68   511.7 2933.45   591.9 2948.37     612 2951.89   652.1  2959.2
#Mann= 3 , 0 , 0
       0      .1       0     306    .045       0     321      .1       0
Bank Sta=306,321
XS Rating Curve= 0 ,0
Exp/Cntr=0.3,0.1

Type RM Length L Ch R = 1 ,59231.8 ,330,336.6,343.2
XS GIS Cut Line= 2
     2096052.219      362531.448     2096237.681      363168.747
#Sta/Elev= 30
       0 2958.29    10.1  2957.7    40.2 2955.07    70.4 2952.91    80.4 2951.95
   100.6 2949.52   120.7 2946.31   130.7 2944.99   160.9 2941.82   201.1 2938.11
   301.7 2929.56   321.8 2926.87   341.9 2923.83     362 2920.36   366.5 2919.81
   372.1 2919.13   381.5 2918.93   382.2 2918.92   392.2 2919.93   432.4 2926.74
   442.5 2928.28   452.6 2929.38   462.6 2929.67   492.8 2928.58   502.8 2929.24
   512.9 2931.21   563.2  2944.8   583.3 2950.45   633.6 2965.66   663.7 2975.09
#Mann= 3 , 0 , 0
       0      .1       0   366.5    .045       0   381.5      .1       0
Bank Sta=366.5,381.5
XS Rating Curve= 0 ,0
Exp/Cntr=0.3,0.1

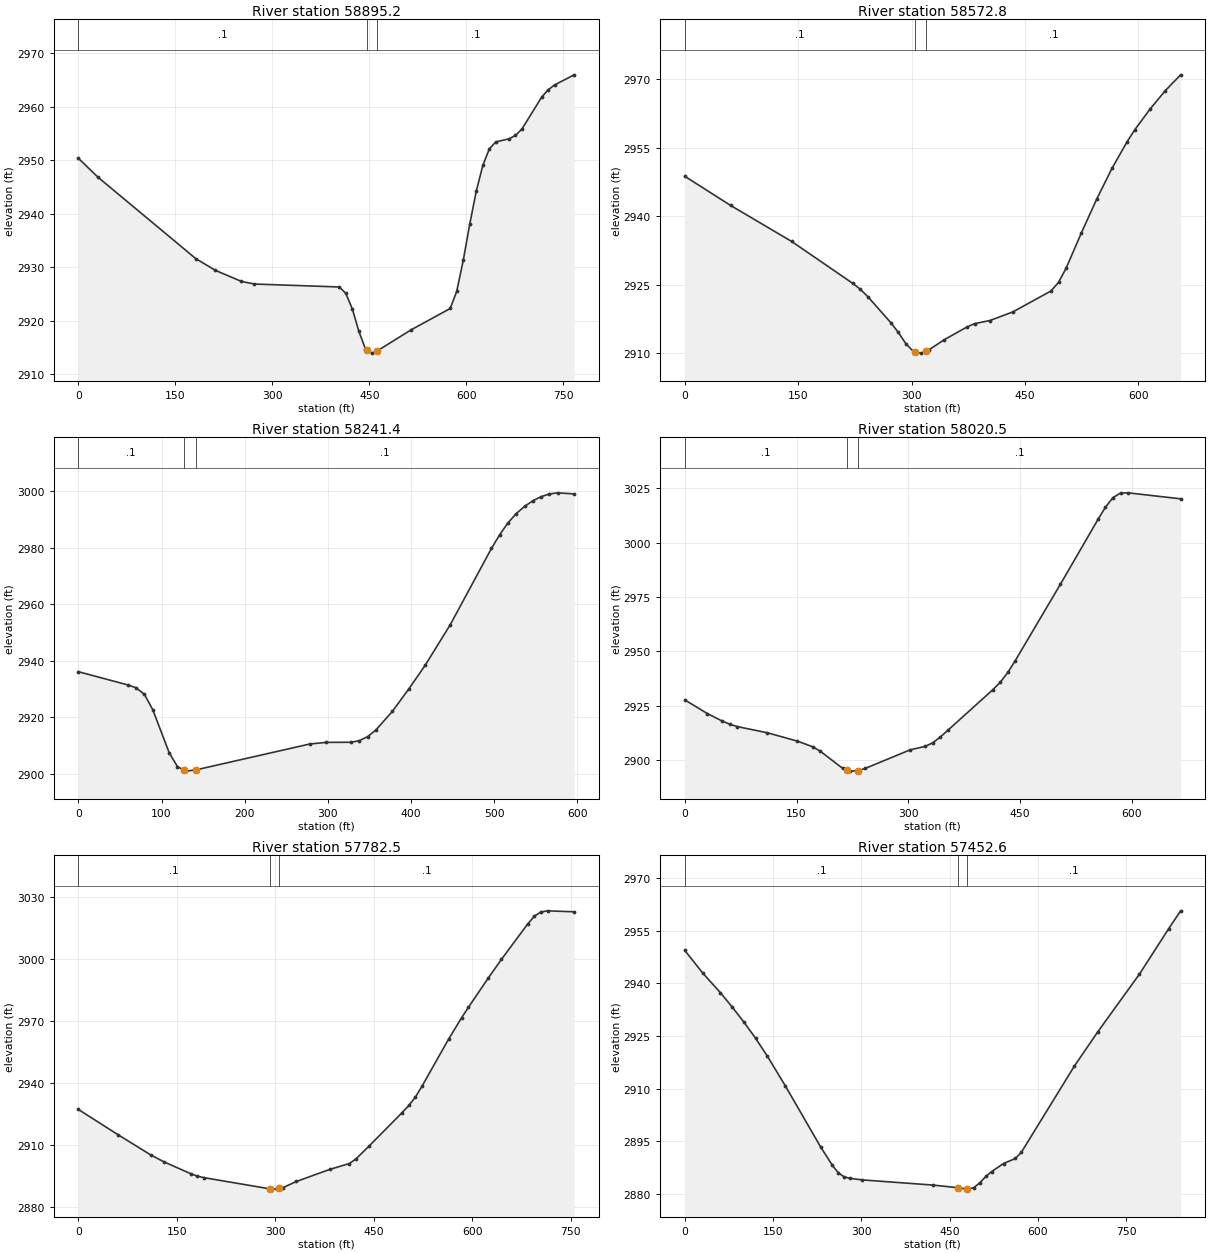
Type RM Length L Ch R = 1 ,58895.2 ,314.2,322,329.8
XS GIS Cut Line= 2
     2095882.142      362565.803     2095858.631      363332.283
#Sta/Elev= 30
       0 2950.39    30.3 2946.86   181.6 2931.64   211.9 2929.45   252.2 2927.38
   272.4 2926.89   403.6 2926.34   413.7 2925.14   423.8 2922.22   433.9 2918.03
     444 2914.78   446.7 2914.56     454 2913.98   461.7 2914.35   514.6 2918.33
   575.1 2922.32   585.2 2925.52   595.3 2931.33   605.4 2938.13   615.5 2944.29
   625.6 2949.06   635.7 2952.17   645.8 2953.45   665.9 2954.02     676 2954.66
   686.1 2955.86   716.4 2961.79   726.5 2963.17   736.6  2964.1   766.8 2965.98
#Mann= 3 , 0 , 0
       0      .1       0   446.7    .045       0   461.7      .1       0
Bank Sta=446.7,461.7
XS Rating Curve= 0 ,0
Exp/Cntr=0.3,0.1

Type RM Length L Ch R = 1 ,58572.8 ,343.4,331.7,320
XS GIS Cut Line= 2
     2095723.534      362564.853     2095487.041      363176.614
#Sta/Elev= 30
       0 2948.75    60.5 2942.38   141.3 2934.49     222 2925.33   232.1 2924.03
   242.2 2922.38   272.4 2916.73   282.5 2914.56   292.6 2912.06   302.7 2910.35
     304 2910.31   312.8 2910.03     319 2910.47   322.9 2910.74   343.1 2912.96
   373.4 2915.77   383.4 2916.49   403.6 2917.17   433.9 2919.05   484.3 2923.63
   494.4 2925.51   504.5 2928.66   524.7 2936.39   544.9 2943.76   565.1  2950.5
   585.2 2956.35   595.3 2958.95   615.5 2963.48   635.7 2967.52   655.9 2970.97
#Mann= 3 , 0 , 0
       0      .1       0     304    .045       0     319      .1       0
Bank Sta=304,319
XS Rating Curve= 0 ,0
Exp/Cntr=0.3,0.1

Type RM Length L Ch R = 1 ,58241.4 ,224.8,220.9,217.1
XS GIS Cut Line= 2
     2095313.362      362562.397     2095394.469      363152.804
#Sta/Elev= 30
       0 2936.07    59.6 2931.38    69.5 2930.36    79.5 2928.02    89.4 2922.66
   109.3 2907.34   119.2 2902.49   126.8 2901.26   129.1 2900.89   141.8 2901.36
   278.1 2910.48     298 2911.06   327.8  2911.1   337.7 2911.66   347.6 2913.07
   357.6 2915.42   377.4 2922.01   397.3 2929.98   417.2 2938.47     447 2952.66
   496.6 2979.69   506.6 2984.59   516.5 2988.74   526.4 2992.01   536.4 2994.55
   546.3 2996.53   556.2 2997.99   566.2 2998.94   576.1 2999.35     596 2998.96
#Mann= 3 , 0 , 0
       0      .1       0   126.8    .045       0   141.8      .1       0
Bank Sta=126.8,141.8
XS Rating Curve= 0 ,0
Exp/Cntr=0.3,0.1

Type RM Length L Ch R = 1 ,58020.5 ,240.2,237.9,235.7
XS GIS Cut Line= 2
     2095059.005      362560.874     2095258.018      363196.136
#Sta/Elev= 30
       0 2927.77    30.3 2921.48    50.4 2918.02    60.5 2916.59    70.6 2915.49
     111 2912.65   151.3 2908.82   171.5 2906.26   181.6 2904.27   211.8 2896.36
   217.8 2895.58   221.9 2895.05   232.8 2895.28   242.1 2896.28   302.6 2904.83
   322.8 2906.42   332.8 2908.05   342.9 2910.66     353 2913.75   413.5 2932.42
   423.6 2935.88   433.7 2940.36   443.8 2945.85   504.3 2980.88   554.8 3010.66
   564.8 3016.27   574.9 3020.68     585 3022.73   595.1 3022.85   665.7  3020.1
#Mann= 3 , 0 , 0
       0      .1       0   217.8    .045       0   232.8      .1       0
Bank Sta=217.8,232.8
XS Rating Curve= 0 ,0
Exp/Cntr=0.3,0.1

Type RM Length L Ch R = 1 ,57782.5 ,327.8,329.9,332
XS GIS Cut Line= 2
     2094780.269      362559.205     2095075.179        363254.2
#Sta/Elev= 30
       0 2927.12    60.4 2914.89   110.7 2905.01   130.9 2901.66   171.1 2896.02
   181.2 2894.84   191.3 2894.09   291.2  2888.7     302 2888.54   306.2 2888.86
   312.1 2889.32   332.2 2892.26   382.5 2898.05   412.7 2900.93   422.8 2903.19
   442.9 2909.44   493.2 2925.62   503.3 2929.04   513.4 2933.14   523.4  2938.4
   563.7 2961.09   583.8 2971.58   593.9 2976.49   624.1 2990.67   644.2 2999.72
   684.5 3016.97   694.6 3020.71   704.6 3022.71   714.7 3023.24     755 3022.77
#Mann= 3 , 0 , 0
       0      .1       0   291.2    .045       0   306.2      .1       0
Bank Sta=291.2,306.2
XS Rating Curve= 0 ,0
Exp/Cntr=0.3,0.1

Type RM Length L Ch R = 1 ,57452.6 ,226.9,230.9,234.8
XS GIS Cut Line= 2
     2094486.362      362557.445     2094738.168      363361.224
#Sta/Elev= 30
       0 2949.41    30.1 2943.04    60.2 2937.41    80.2 2933.35   100.3    2929
   120.3 2924.36   140.4 2919.24   170.5 2910.89   230.6 2893.45   250.7 2888.16
   260.7 2886.06   270.7 2884.87   280.8 2884.45   300.8 2884.02   421.2 2882.54
   463.6  2881.8   478.6 2881.43   481.3 2881.38   491.3 2881.84   501.4 2883.23
   511.4 2884.98   521.4  2886.4   541.5 2888.68   561.5 2890.11   571.6 2891.84
   661.8 2916.44   701.9 2926.29   772.1 2942.59   822.2 2955.65   842.3 2960.69
#Mann= 3 , 0 , 0
       0      .1       0   463.6    .045       0   478.6      .1       0
Bank Sta=463.6,478.6
XS Rating Curve= 0 ,0
Exp/Cntr=0.3,0.1

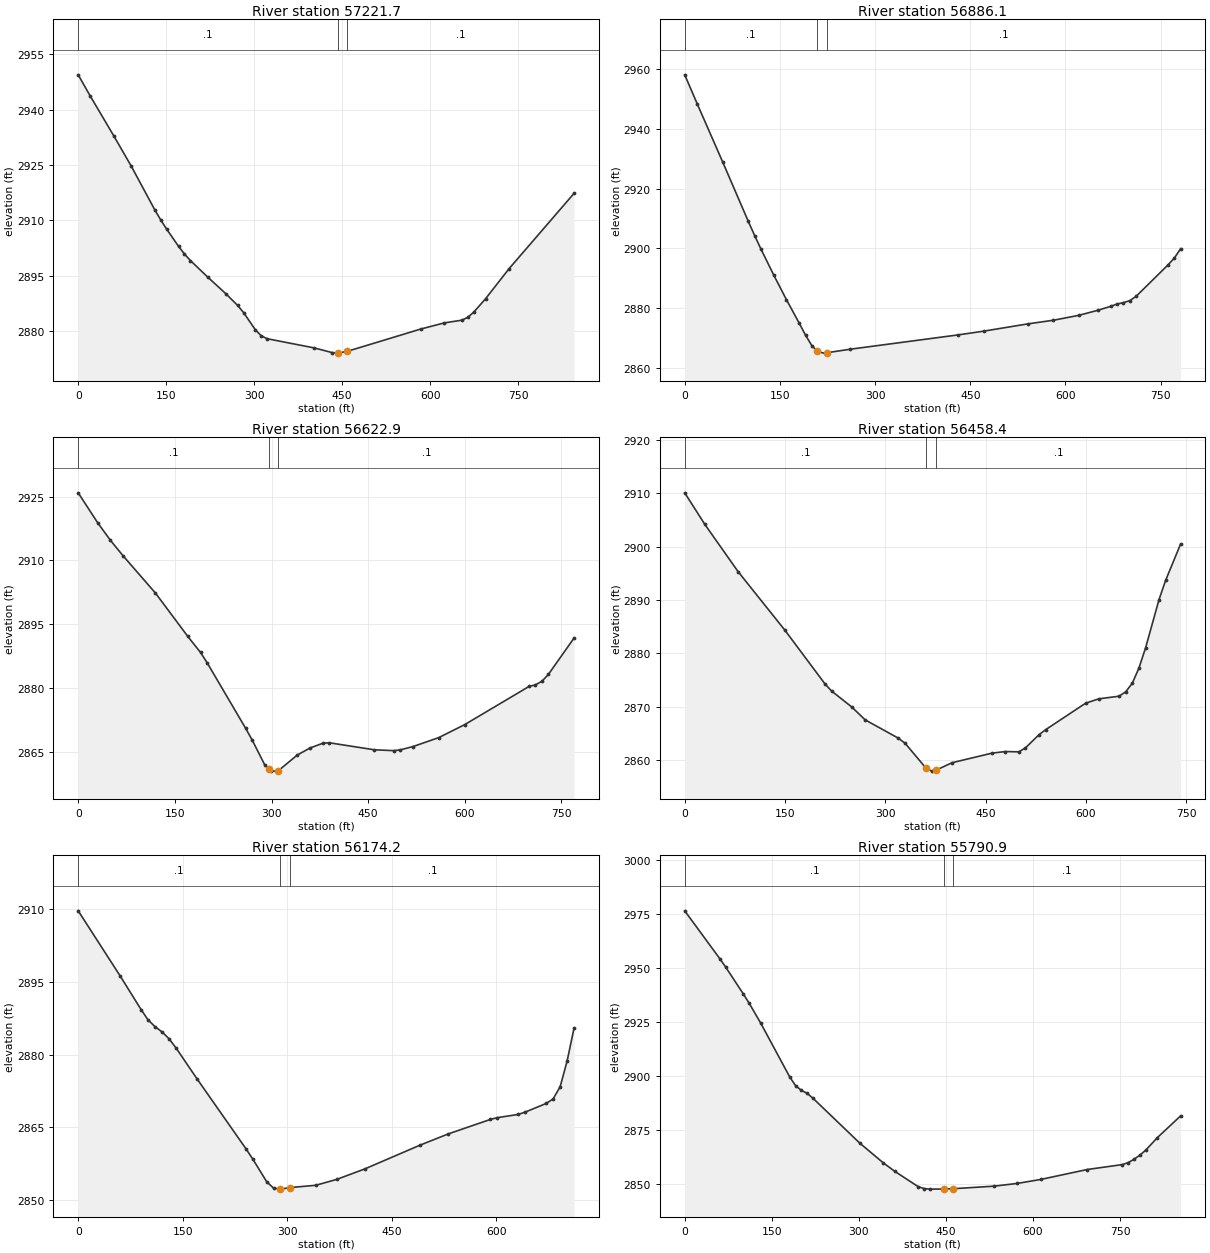
Type RM Length L Ch R = 1 ,57221.7 ,342.5,335.7,328.8
XS GIS Cut Line= 2
     2094347.648      362612.316     2094457.271      363450.427
#Sta/Elev= 30
       0 2949.46    20.1 2943.82    60.4 2932.97    90.6 2924.64   130.8 2912.76
   140.9 2910.04   150.9 2907.57   171.1 2902.93   181.1 2900.86   191.2  2899.1
   221.4  2894.5   251.6  2890.1   271.7 2886.92   281.8 2884.99   301.9 2880.32
   311.9 2878.69     322 2877.89   402.5 2875.39   432.7 2874.13   442.8 2873.98
   443.2 2873.99   458.2 2874.45   583.6  2880.5   623.9 2882.18   654.1 2882.92
   664.1  2883.7   674.2  2885.1   694.3 2888.73   734.6 2896.93   845.2 2917.33
#Mann= 3 , 0 , 0
       0      .1       0   443.2    .045       0   458.2      .1       0
Bank Sta=443.2,458.2
XS Rating Curve= 0 ,0
Exp/Cntr=0.3,0.1

Type RM Length L Ch R = 1 ,56886.1 ,267.4,263,258.5
XS GIS Cut Line= 2
     2093996.744      362781.821     2094315.035      363495.597
#Sta/Elev= 30
       0 2958.04      20 2948.17    60.1 2928.76   100.2 2909.03   110.2  2904.3
   120.2 2899.75   140.3 2891.09   160.3 2882.87   180.4 2875.02   190.4    2871
   200.4 2867.48   208.9 2865.68   210.4 2865.36   220.4    2865   223.9 2865.13
   260.5  2866.3   430.8 2871.09   470.9 2872.34   541.1 2874.79   581.1    2876
   621.2 2877.64   651.3 2879.34   671.3 2880.64   681.3 2881.42   691.4 2881.88
   701.4 2882.54   711.4    2884   761.5 2894.47   771.5 2896.76   781.5 2899.92
#Mann= 3 , 0 , 0
       0      .1       0   208.9    .045       0   223.9      .1       0
Bank Sta=208.9,223.9
XS Rating Curve= 0 ,0
Exp/Cntr=0.3,0.1

Type RM Length L Ch R = 1 ,56622.9 ,162.7,164.3,165.9
XS GIS Cut Line= 2
     2093722.682      362914.206      2094166.96      363542.621
#Sta/Elev= 30
       0 2925.93      30 2918.93      50 2914.74      70 2911.04   119.9 2902.33
   169.9 2892.16   189.9 2888.34   199.9 2885.97   259.9 2870.48   269.9 2867.76
   289.8 2861.79   295.8 2860.97   299.8 2860.42   309.8 2860.41   310.8 2860.53
   339.8 2864.18   359.8 2865.86   379.8 2866.98   389.8 2867.08   459.8 2865.43
   489.8 2865.23   499.7 2865.41   519.7  2866.2   559.7 2868.31   599.7 2871.35
   699.6 2880.34   709.6 2880.72   719.6 2881.55   729.6 2883.16   769.6 2891.76
#Mann= 3 , 0 , 0
       0      .1       0   295.8    .045       0   310.8      .1       0
Bank Sta=295.8,310.8
XS Rating Curve= 0 ,0
Exp/Cntr=0.3,0.1

Type RM Length L Ch R = 1 ,56458.4 ,277.4,284.3,291.2
XS GIS Cut Line= 3
     2093598.708      362974.092     2093987.516      363602.986
     2093988.721      363604.936
#Sta/Elev= 30
       0 2910.09      30 2904.19    79.9 2895.31   149.9 2884.34   209.8 2874.28
   219.8 2872.94   249.8 2869.97   269.8 2867.56   319.7 2864.11   329.7 2863.16
   361.1 2858.47   369.7 2857.95   376.1 2858.14   399.7 2859.52   459.6 2861.32
   479.6 2861.62   499.6 2861.56   509.6  2862.3   529.6 2864.74   539.6  2865.7
   599.5 2870.67   619.5  2871.5   649.4 2871.98   659.4 2872.79   669.4 2874.41
   679.4 2877.28   689.4 2881.08   709.4 2890.09   719.4 2893.73   741.7 2900.51
#Mann= 3 , 0 , 0
       0      .1       0   361.1    .045       0   376.1      .1       0
Bank Sta=361.1,376.1
XS Rating Curve= 0 ,0
Exp/Cntr=0.3,0.1

Type RM Length L Ch R = 1 ,56174.2 ,384.5,383.3,382.6
XS GIS Cut Line= 2
     2093476.078      363033.328     2093667.589      363718.886
#Sta/Elev= 30
       0 2909.66    60.2 2896.22    90.2 2889.29   100.2 2887.16   110.3 2885.74
   120.3 2884.67   130.3 2883.27   140.4 2881.36   170.4 2875.01   240.6 2860.58
   250.6 2858.41   270.7 2853.71   280.7 2852.38   289.6 2852.23   290.7 2852.21
   304.6 2852.54   340.9    2853   370.9 2854.21     411 2856.36   491.2 2861.32
   531.4 2863.62   591.5 2866.59   601.5 2866.96   631.6 2867.63   641.6 2868.11
   671.7 2869.89   681.7 2870.83   691.8 2873.35   701.8 2878.67   711.8 2885.49
#Mann= 3 , 0 , 0
       0      .1       0   289.6    .045       0   304.6      .1       0
Bank Sta=289.6,304.6
XS Rating Curve= 0 ,0
Exp/Cntr=0.3,0.1

Type RM Length L Ch R = 1 ,55790.9 ,329.7,333.8,336.9
XS GIS Cut Line= 2
     2093089.154      363024.154      2093319.05      363847.121
#Sta/Elev= 30
       0 2976.61    60.3 2954.49    70.4 2950.62   100.5  2938.3   110.6    2934
   130.7  2924.7     181 2899.63     191 2895.63     201 2893.48   211.1 2892.03
   221.2 2889.75   301.6 2869.02   341.8 2859.95   361.9 2855.96   402.1 2848.89
   412.2 2847.98   422.2 2847.71     447 2847.76     462 2847.89   532.8 2849.08
     573 2850.35   613.2 2852.18   693.6  2856.8     754 2859.07     764 2859.96
     774 2861.51   784.1 2863.42   794.2 2865.71   814.3 2871.54   854.5 2881.64
#Mann= 3 , 0 , 0
       0      .1       0     447    .045       0     462      .1       0
Bank Sta=447,462
XS Rating Curve= 0 ,0
Exp/Cntr=0.3,0.1