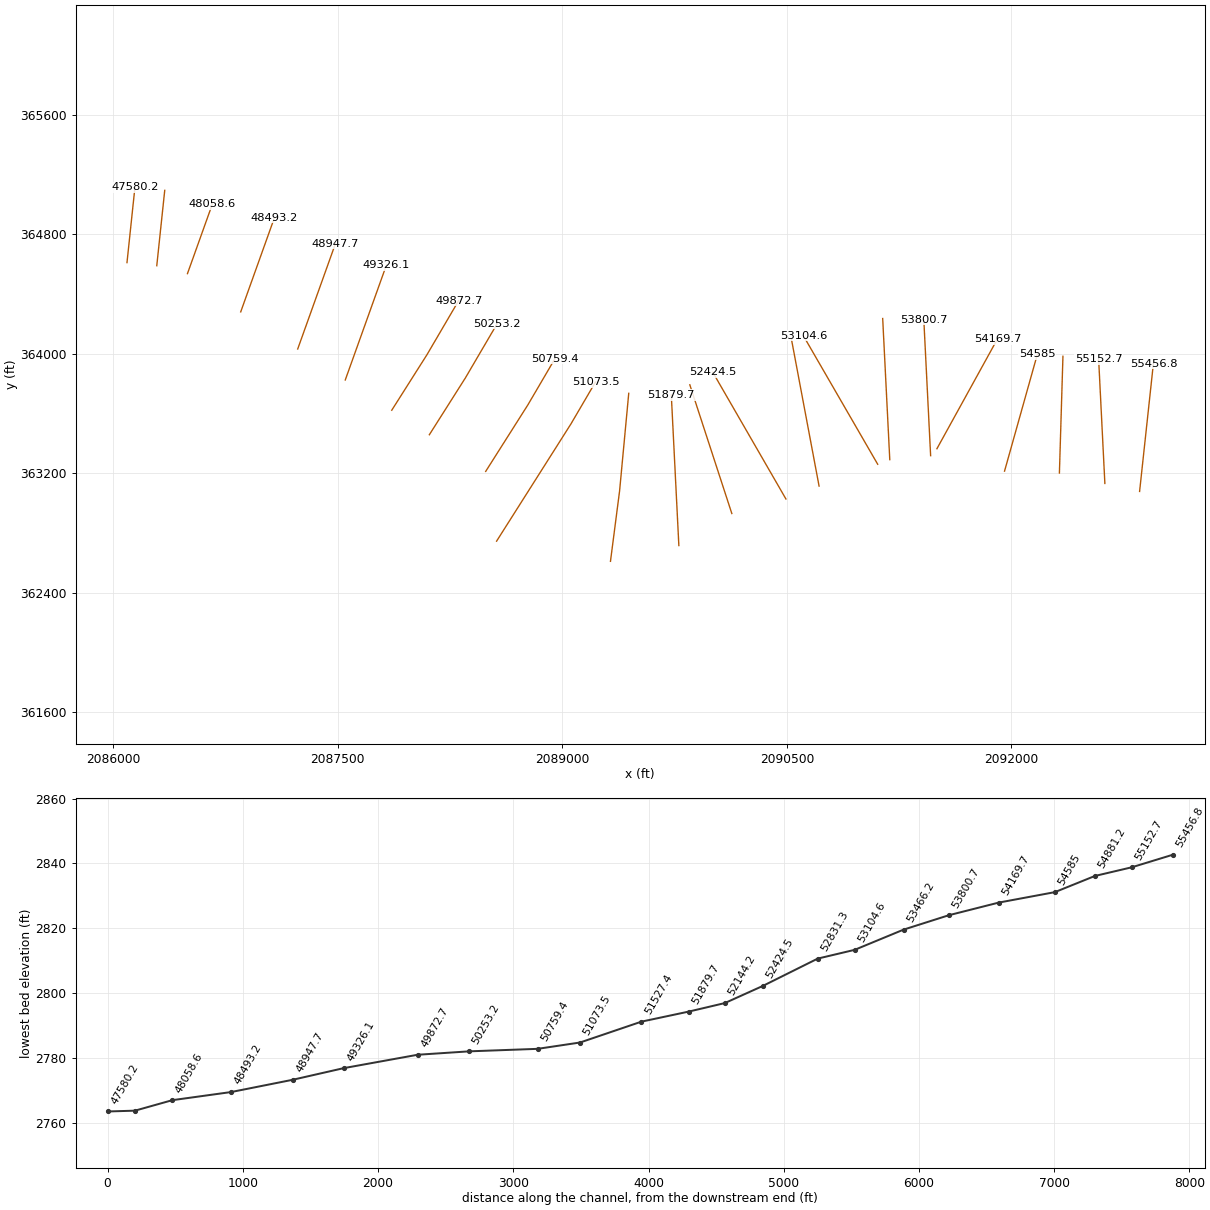
HEC-RAS study LittleClCk.prj: LittleClCk

--- LittleClCk.g01 (geometry) --- (continued)

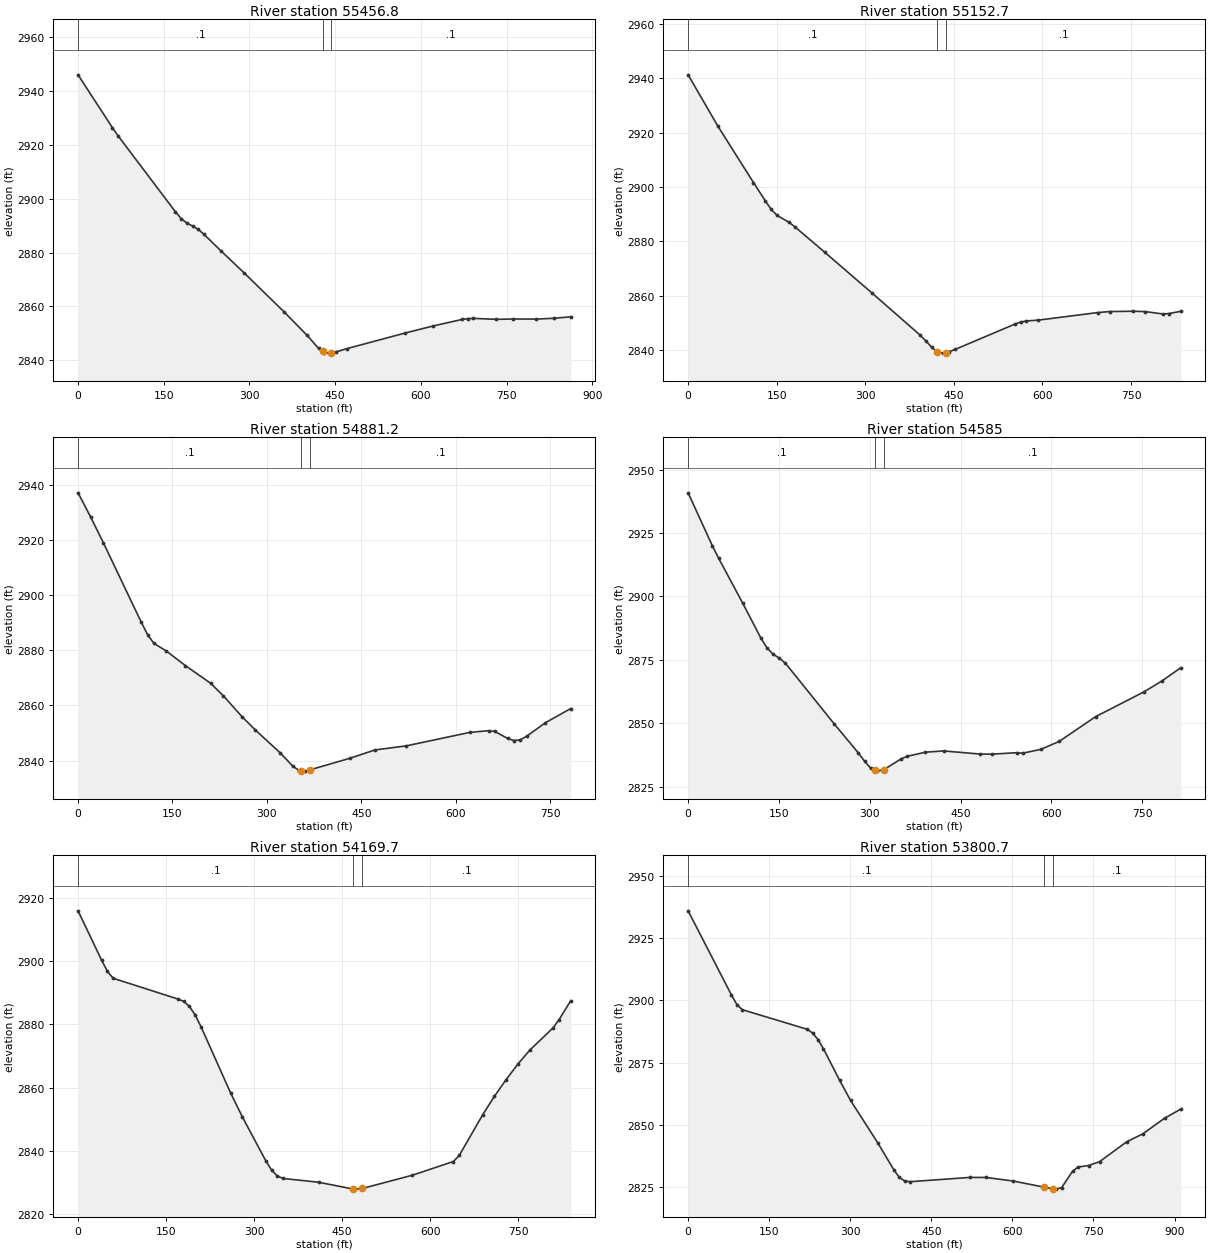
Type RM Length L Ch R = 1 ,55456.8 ,300.5,304.1,307.7
XS GIS Cut Line= 2
     2092855.635      363078.043     2092947.841      363935.312
#Sta/Elev= 30
       0 2945.97    60.2 2926.34    70.2 2923.29   170.4 2895.15   180.5 2892.62
   190.5 2890.93   200.5 2889.88   210.5 2888.57   220.6 2886.74   250.6 2880.54
   290.8 2872.44   360.9 2857.94     401 2849.26   421.1 2844.41     428 2843.36
   431.1 2842.89   441.1 2842.69     443 2842.77   451.2 2843.13   471.2  2844.4
   571.5  2850.1   621.6 2852.78   671.7 2855.17   681.8 2855.49   691.8 2855.59
   731.9 2855.23     762 2855.36   802.1 2855.32   832.1 2855.62   862.2 2856.16
#Mann= 3 , 0 , 0
       0      .1       0     428    .045       0     443      .1       0
Bank Sta=428,443
XS Rating Curve= 0 ,0
Exp/Cntr=0.3,0.1

Type RM Length L Ch R = 1 ,55152.7 ,273.4,271.6,269.7
XS GIS Cut Line= 2
     2092623.765      363131.552     2092582.108      363964.701
#Sta/Elev= 30
       0  2941.3    50.2 2922.46   110.6 2901.65   130.7 2894.91   140.7 2891.73
   150.8  2889.5   170.9    2887   180.9  2885.3   231.2 2875.99   311.6 2860.91
     392 2845.61     402 2843.47   412.1 2841.06   421.2 2839.41   422.1 2839.25
   432.2 2838.82   436.2 2839.03   442.2 2839.35   452.3 2840.21   552.8 2849.46
   562.8 2850.23   572.9 2850.67     593 2850.98   693.5 2853.75   713.6 2854.13
   753.8 2854.24   773.9 2854.12     804 2853.24   814.1 2853.39   834.2 2854.22
#Mann= 3 , 0 , 0
       0      .1       0   421.2    .045       0   436.2      .1       0
Bank Sta=421.2,436.2
XS Rating Curve= 0 ,0
Exp/Cntr=0.3,0.1

Type RM Length L Ch R = 1 ,54881.2 ,301.8,296.2,290.6
XS GIS Cut Line= 2
     2092320.126      363201.622     2092343.753      363983.855
#Sta/Elev= 30
       0 2937.24    20.1 2928.42    40.1 2919.17   100.3  2890.3   110.4 2885.76
   120.4 2882.58   140.5 2879.75   170.6 2874.48   210.7 2868.06   230.8 2863.51
   260.9 2855.84   280.9 2851.26   321.1  2842.8   341.1 2837.97   351.2 2836.38
   353.7 2836.32   361.2 2836.16   368.7 2836.65   431.4  2840.8   471.6 2843.85
   521.7 2845.35   622.1 2850.22   652.2 2850.85   662.2 2850.56   682.3 2848.04
   692.3 2847.28   702.3 2847.53   712.4 2848.79   742.5 2853.75   782.6 2858.89
#Mann= 3 , 0 , 0
       0      .1       0   353.7    .045       0   368.7      .1       0
Bank Sta=353.7,368.7
XS Rating Curve= 0 ,0
Exp/Cntr=0.3,0.1

Type RM Length L Ch R = 1 ,54585   ,420.3,415.3,410.2
XS GIS Cut Line= 2
     2091953.697      363214.146     2092173.019      363997.575
#Sta/Elev= 30
       0 2940.85    40.2  2919.9    50.2 2915.16    90.4 2897.26   120.5 2883.45
   130.6 2879.61   140.6  2877.2   150.7  2875.7   160.7  2873.7     241 2849.88
   281.2 2838.33   291.3 2835.11   301.3  2832.4   308.5 2831.53   311.4 2831.18
   323.5 2831.79   351.5 2835.98   361.6    2837   391.7 2838.64   421.8 2839.14
   482.1 2837.91   502.2 2837.87   542.4 2838.44   552.4 2838.25   582.5 2839.75
   612.7 2842.89   672.9 2852.64   753.3 2862.48   783.4 2866.86   813.6 2871.93
#Mann= 3 , 0 , 0
       0      .1       0   308.5    .045       0   323.5      .1       0
Bank Sta=308.5,323.5
XS Rating Curve= 0 ,0
Exp/Cntr=0.3,0.1

Type RM Length L Ch R = 1 ,54169.7 ,356.6,369,381.5
XS GIS Cut Line= 2
     2091502.173      363364.396     2091906.325      364099.888
#Sta/Elev= 30
       0  2915.9      40 2900.36      50 2896.78    59.9 2894.58   169.8 2888.05
   179.8  2887.3   189.8 2885.69   199.8 2882.89   209.8 2879.14   259.8 2858.38
   279.7 2850.85   319.7 2836.95   329.7 2833.96   339.7 2832.06   349.7 2831.32
   409.6 2830.14   469.2 2827.97   469.6 2827.96   484.2 2828.16   569.5 2832.36
   639.4 2836.69   649.4 2838.62   689.4  2851.5   709.3 2857.31   729.3  2862.6
   749.3 2867.48   769.3 2871.85   809.2 2878.92   819.2 2881.47   839.2 2887.49
#Mann= 3 , 0 , 0
       0      .1       0   469.2    .045       0   484.2      .1       0
Bank Sta=469.2,484.2
XS Rating Curve= 0 ,0
Exp/Cntr=0.3,0.1

Type RM Length L Ch R = 1 ,53800.7 ,332.6,334.5,335.8
XS GIS Cut Line= 2
     2091460.108      363317.785     2091414.589       364228.15
#Sta/Elev= 30
       0 2936.09    80.1 2902.25    90.2 2898.36   100.2  2896.3   220.4 2888.41
   230.4  2886.9   240.4 2884.24   250.4 2880.55   280.5  2867.8   300.5 2859.79
   350.6 2842.79   380.6 2831.87   390.6 2828.84   400.7 2827.35   410.7 2827.06
   520.9 2828.78   550.9 2828.77     601 2827.35   659.3 2824.84   674.3 2824.25
   681.1 2824.07   691.1 2824.69   711.2 2831.24   721.2 2832.97   741.2 2833.58
   761.2 2835.12   811.3  2843.1   841.4 2846.34   881.4  2852.6   911.5 2856.29
#Mann= 3 , 0 , 0
       0      .1       0   659.3    .045       0   674.3      .1       0
Bank Sta=659.3,674.3
XS Rating Curve= 0 ,0
Exp/Cntr=0.3,0.1

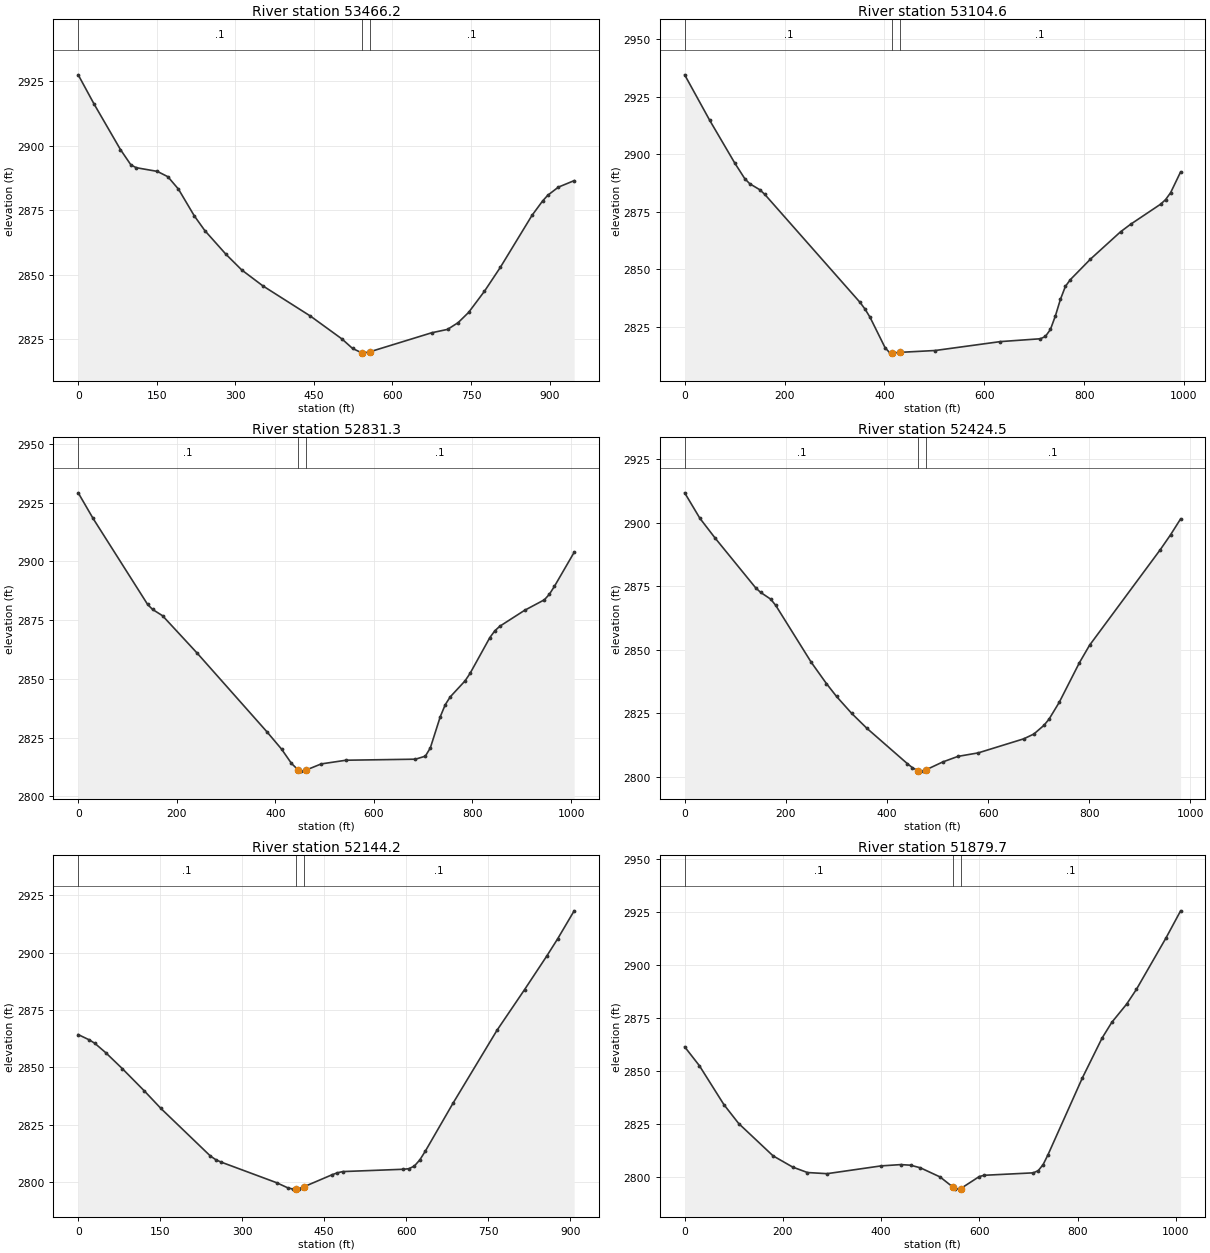
Type RM Length L Ch R = 1 ,53466.2 ,351.8,361.5,369.9
XS GIS Cut Line= 2
     2091187.267      363291.172     2091139.981      364236.895
#Sta/Elev= 30
       0  2927.5    30.2 2916.21    80.6 2898.55   100.7 2892.57   110.8 2891.51
   151.1 2890.07   171.2 2888.01   191.4  2883.2   221.6 2872.86   241.8 2867.12
   282.1 2857.95   312.3 2851.86   352.6  2845.7   443.2 2834.02   503.7 2825.11
   523.8 2821.45   541.6 2819.74     544 2819.64   556.6 2820.14   674.9 2827.53
   705.1 2828.84   725.3 2831.44   745.4 2835.42   775.7 2843.64   805.9 2852.86
   866.3 2872.99   886.5 2878.57   896.5 2880.82   916.7 2883.97   946.9 2886.49
#Mann= 3 , 0 , 0
       0      .1       0   541.6    .045       0   556.6      .1       0
Bank Sta=541.6,556.6
XS Rating Curve= 0 ,0
Exp/Cntr=0.3,0.1

Type RM Length L Ch R = 1 ,53104.6 ,281.7,273.3,265
XS GIS Cut Line= 2
      2091106.61      363260.255     2090610.701      364120.957
#Sta/Elev= 30
       0 2934.45    50.2 2914.64   100.3 2896.09   120.4 2889.28   130.4 2887.08
   150.5 2884.47   160.5 2882.44   351.2 2835.49   361.2 2832.57   371.2 2829.03
   401.4 2815.78   411.4 2813.42   415.5 2813.48   430.5 2813.75   501.7 2814.56
   632.1 2818.43   712.4 2819.67   722.4 2820.66   732.5  2823.7   742.5 2829.62
   752.5 2836.77   762.6 2842.48   772.6 2845.42   812.7  2854.3   872.9 2866.17
     893 2869.44   953.2 2878.19   963.2 2880.18   973.3 2883.21   993.3 2892.25
#Mann= 3 , 0 , 0
       0      .1       0   415.5    .045       0   430.5      .1       0
Bank Sta=415.5,430.5
XS Rating Curve= 0 ,0
Exp/Cntr=0.3,0.1

Type RM Length L Ch R = 1 ,52831.3 ,399.4,406.8,414.3
XS GIS Cut Line= 2
     2090715.106       363114.12       2090529.7      364103.214
#Sta/Elev= 30
       0 2929.16    30.2 2918.25   140.9 2881.64     151 2879.52   171.1 2876.86
   241.5 2860.91   382.4 2827.58   412.6 2820.09   432.7 2814.01   446.4 2811.22
   452.8 2810.72   461.4  2811.1   493.1 2813.79   543.4 2815.36   684.3  2815.8
   704.4 2817.09   714.5 2820.63   734.6 2833.86   744.7 2838.97   754.7 2842.28
   784.9 2849.13     795 2852.29   835.2 2867.54   845.3 2870.42   855.4 2872.38
   905.7 2879.15   945.9 2883.64     956 2885.99   966.1  2889.3  1006.3 2903.84
#Mann= 3 , 0 , 0
       0      .1       0   446.4    .045       0   461.4      .1       0
Bank Sta=446.4,461.4
XS Rating Curve= 0 ,0
Exp/Cntr=0.3,0.1

Type RM Length L Ch R = 1 ,52424.5 ,284.9,280.2,275.5
XS GIS Cut Line= 2
     2090493.681       363027.73     2090004.792      363877.772
#Sta/Elev= 30
       0 2911.82      30 2901.82      60 2894.06   140.1 2874.49   150.1 2872.65
   170.1 2869.97   180.1  2867.5   250.2 2845.14   280.2 2836.77   300.2 2831.69
   330.2 2825.02   360.2 2819.16   440.3 2805.23   450.3 2803.64   461.9 2802.42
   470.3 2802.29   476.9 2802.78   510.3  2805.9   540.3 2808.09   580.4 2809.47
   670.4    2815   690.4 2816.89   710.4 2820.32   720.4 2822.74   740.5 2829.34
   780.5 2844.97   800.5 2851.82   940.6 2889.51   960.6 2895.28   980.6 2901.57
#Mann= 3 , 0 , 0
       0      .1       0   461.9    .045       0   476.9      .1       0
Bank Sta=461.9,476.9
XS Rating Curve= 0 ,0
Exp/Cntr=0.3,0.1

Type RM Length L Ch R = 1 ,52144.2 ,271.1,264.5,258
XS GIS Cut Line= 2
     2090132.444      362930.149     2089851.897       363792.83
#Sta/Elev= 30
       0 2864.33    20.2 2862.03    30.2 2860.56    50.4 2856.44    80.6 2849.52
     121 2839.79   151.2 2832.18   241.9 2811.42     252  2809.8   262.1 2808.74
   362.9 2799.83     383 2797.63   393.1 2797.03   397.9 2797.12   403.2 2797.22
   412.9 2798.06   463.7 2803.22   473.7 2804.11   483.8 2804.67   594.7 2805.68
   604.8 2805.92   614.8 2807.06   624.9 2809.77     635 2813.59   685.4 2834.36
     766 2866.18   816.4 2883.88   856.8 2898.42   876.9 2905.98   907.2 2918.22
#Mann= 3 , 0 , 0
       0      .1       0   397.9    .045       0   412.9      .1       0
Bank Sta=397.9,412.9
XS Rating Curve= 0 ,0
Exp/Cntr=0.3,0.1

Type RM Length L Ch R = 1 ,51879.7 ,355.5,352.3,349.1
XS GIS Cut Line= 2
      2089778.72      362715.453     2089728.285      363724.157
#Sta/Elev= 30
       0 2861.56      30 2852.64      80 2834.26     110 2825.38     180 2810.13
     220 2804.83     250 2802.26     290 2801.72     400 2805.39     440    2806
     460 2805.72     480 2804.49     520 2800.19   546.8  2795.3     550 2794.64
     560 2794.43   561.8 2794.64     600 2800.37     610 2800.96     710 2802.11
     720 2803.15     730 2806.01     740  2810.7     810 2846.94     850 2865.67
     870 2873.16     900 2881.68     920 2888.66     980 2912.82    1010  2925.7
#Mann= 3 , 0 , 0
       0      .1       0   546.8    .045       0   561.8      .1       0
Bank Sta=546.8,561.8
XS Rating Curve= 0 ,0
Exp/Cntr=0.3,0.1

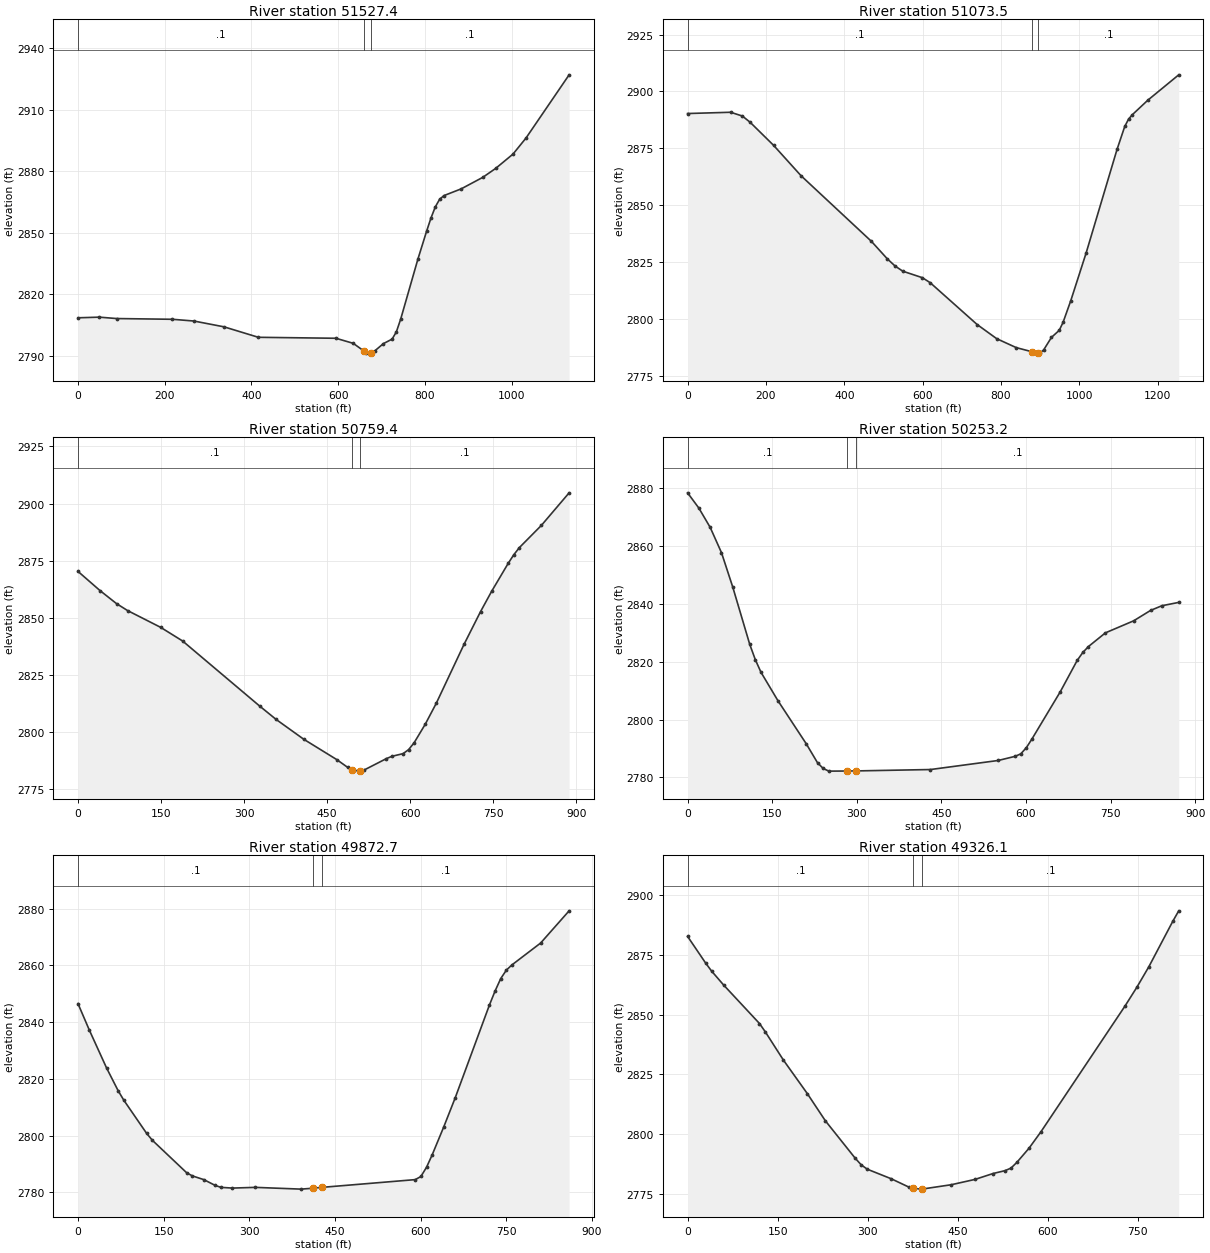
Type RM Length L Ch R = 1 ,51527.4 ,464.2,453.9,443.3
XS GIS Cut Line= 3
     2089322.044      362609.868     2089382.901      363081.329
     2089444.053      363735.624
#Sta/Elev= 30
       0 2808.55    49.5 2808.86    89.1 2808.18   217.9 2807.82   267.4 2806.97
   336.7 2804.14     416 2799.03   594.8 2798.56   634.7 2796.09   659.6  2792.3
   664.6 2791.57   674.5 2791.31   674.6 2791.32   684.5 2792.43   704.4 2795.97
   724.3 2798.14   734.2  2801.7   744.2 2807.96     784 2837.31     804 2850.87
   813.9 2857.19   823.9 2862.64   833.8 2866.34   843.8 2868.16   883.6 2871.45
   933.4 2877.07   963.2 2881.44  1003.1 2888.42    1033 2896.23  1132.5 2927.09
#Mann= 3 , 0 , 0
       0      .1       0   659.6    .045       0   674.6      .1       0
Bank Sta=659.6,674.6
XS Rating Curve= 0 ,0
Exp/Cntr=0.3,0.1

Type RM Length L Ch R = 1 ,51073.5 ,314.6,314.1,313.8
XS GIS Cut Line= 3
     2088561.513         362745.     2089057.911      363530.346
     2089221.739      363810.924
#Sta/Elev= 30
       0  2890.3   109.9 2890.86   139.9  2889.2   159.8 2886.44   219.8 2876.27
   289.7 2862.93   469.5 2834.04   509.5 2826.45   529.5 2823.25   549.4 2820.94
   599.4 2818.08   619.4 2815.88   739.3 2797.47   789.2 2791.25   839.2 2787.31
   879.9 2785.47   894.9 2784.93   899.1 2784.89   909.1  2786.3   929.1 2791.83
   948.8  2794.9   958.6  2798.4   978.3 2807.94  1017.7 2829.03  1096.4 2874.48
  1116.1  2884.6    1126 2887.88  1135.8 2889.83  1175.2 2896.19    1254 2907.33
#Mann= 3 , 0 , 0
       0      .1       0   879.9    .045       0   894.9      .1       0
Bank Sta=879.9,894.9
XS Rating Curve= 0 ,0
Exp/Cntr=0.3,0.1

Type RM Length L Ch R = 1 ,50759.4 ,505,506.2,510.2
XS GIS Cut Line= 3
     2088488.686      363212.391     2088770.323      363657.967
     2088951.789      363968.753
#Sta/Elev= 30
       0 2870.33    39.8 2861.93    69.6 2856.23    89.5  2853.2   149.2 2845.86
     189 2839.87   328.2 2811.39     358 2805.53   407.8 2796.88   467.4 2787.98
   487.3 2784.54   494.6 2783.65   507.2 2782.94   509.6 2783.07   517.2 2783.48
   557.1 2788.43   567.1 2789.43   587.1 2790.59   597.1 2792.34   607.1 2795.36
   627.1 2803.43   647.1 2812.64   697.1 2838.35   727.1 2852.76     747 2861.58
     777 2873.86     787 2877.58     797  2880.7     837 2890.48     887  2904.7
#Mann= 3 , 0 , 0
       0      .1       0   494.6    .045       0   509.6      .1       0
Bank Sta=494.6,509.6
XS Rating Curve= 0 ,0
Exp/Cntr=0.3,0.1

Type RM Length L Ch R = 1 ,50253.2 ,377.9,380.5,378.1
XS GIS Cut Line= 3
      2088112.51      363458.159     2088353.325       363839.15
      2088565.21      364202.033
#Sta/Elev= 30
       0 2878.31      20 2873.03    40.1 2866.36    60.1 2857.64    80.1 2845.75
   110.2 2825.97   120.2 2820.62   130.2  2816.3   160.2  2806.5   210.3 2791.65
   230.4 2785.06   240.4  2783.1   250.4 2782.17   283.5 2782.21   298.5 2782.24
   430.7 2782.72   550.8 2785.85   580.8 2787.28   590.8 2788.14   600.8  2790.3
   610.8 2793.33   660.8 2809.57   690.8  2820.4   700.8 2823.16   710.8 2825.21
   740.9 2829.94   790.9 2834.09   820.9 2837.68   840.9  2839.3   870.9 2840.46
#Mann= 3 , 0 , 0
       0      .1       0   283.5    .045       0   298.5      .1       0
Bank Sta=283.5,298.5
XS Rating Curve= 0 ,0
Exp/Cntr=0.3,0.1

Type RM Length L Ch R = 1 ,49872.7 ,542,546.7,551.4
XS GIS Cut Line= 3
     2087861.332      363622.263     2088096.915      363994.976
     2088308.327      364357.049
#Sta/Elev= 30
       0  2846.5      20 2837.11    50.1 2823.81    70.2 2815.86    80.2 2812.48
   120.2 2800.78   130.3 2798.33   190.4 2786.88   200.4 2785.78   220.5 2784.46
   240.5 2782.41   250.5 2781.74   270.6 2781.49   310.6 2781.74   390.8 2781.12
   411.7 2781.44   426.7 2781.73   590.7 2784.47   600.6 2785.57   610.6 2788.88
   620.6 2793.31   640.6 2803.03   660.6 2813.25   720.4 2845.88   730.4 2850.88
   740.4 2855.31   750.4 2858.33   760.4 2860.19   810.3 2867.84   860.2 2879.19
#Mann= 3 , 0 , 0
       0      .1       0   411.7    .045       0   426.7      .1       0
Bank Sta=411.7,426.7
XS Rating Curve= 0 ,0
Exp/Cntr=0.3,0.1

Type RM Length L Ch R = 1 ,49326.1 ,379.4,378.3,377.3
XS GIS Cut Line= 2
     2087550.944      363825.049     2087826.007      364595.804
#Sta/Elev= 30
       0 2882.74    29.9 2871.66    39.9 2868.27    59.9 2862.45   119.8  2846.3
   129.7 2842.74   159.7 2830.98   199.6 2816.94   229.5 2805.62   279.4  2789.9
   289.4 2787.14   299.4 2785.34   339.3 2781.34   369.3 2777.78   376.2 2777.33
   389.2    2777   391.2 2777.04   439.1 2778.83     479 2781.07     509 2783.53
   528.9 2784.73   538.9  2785.8   548.9 2788.26   568.9 2794.11   588.8    2801
   728.6 2853.51   748.5 2861.42   768.5 2870.01   808.4 2889.03   818.4 2893.45
#Mann= 3 , 0 , 0
       0      .1       0   376.2    .045       0   391.2      .1       0
Bank Sta=376.2,391.2
XS Rating Curve= 0 ,0
Exp/Cntr=0.3,0.1

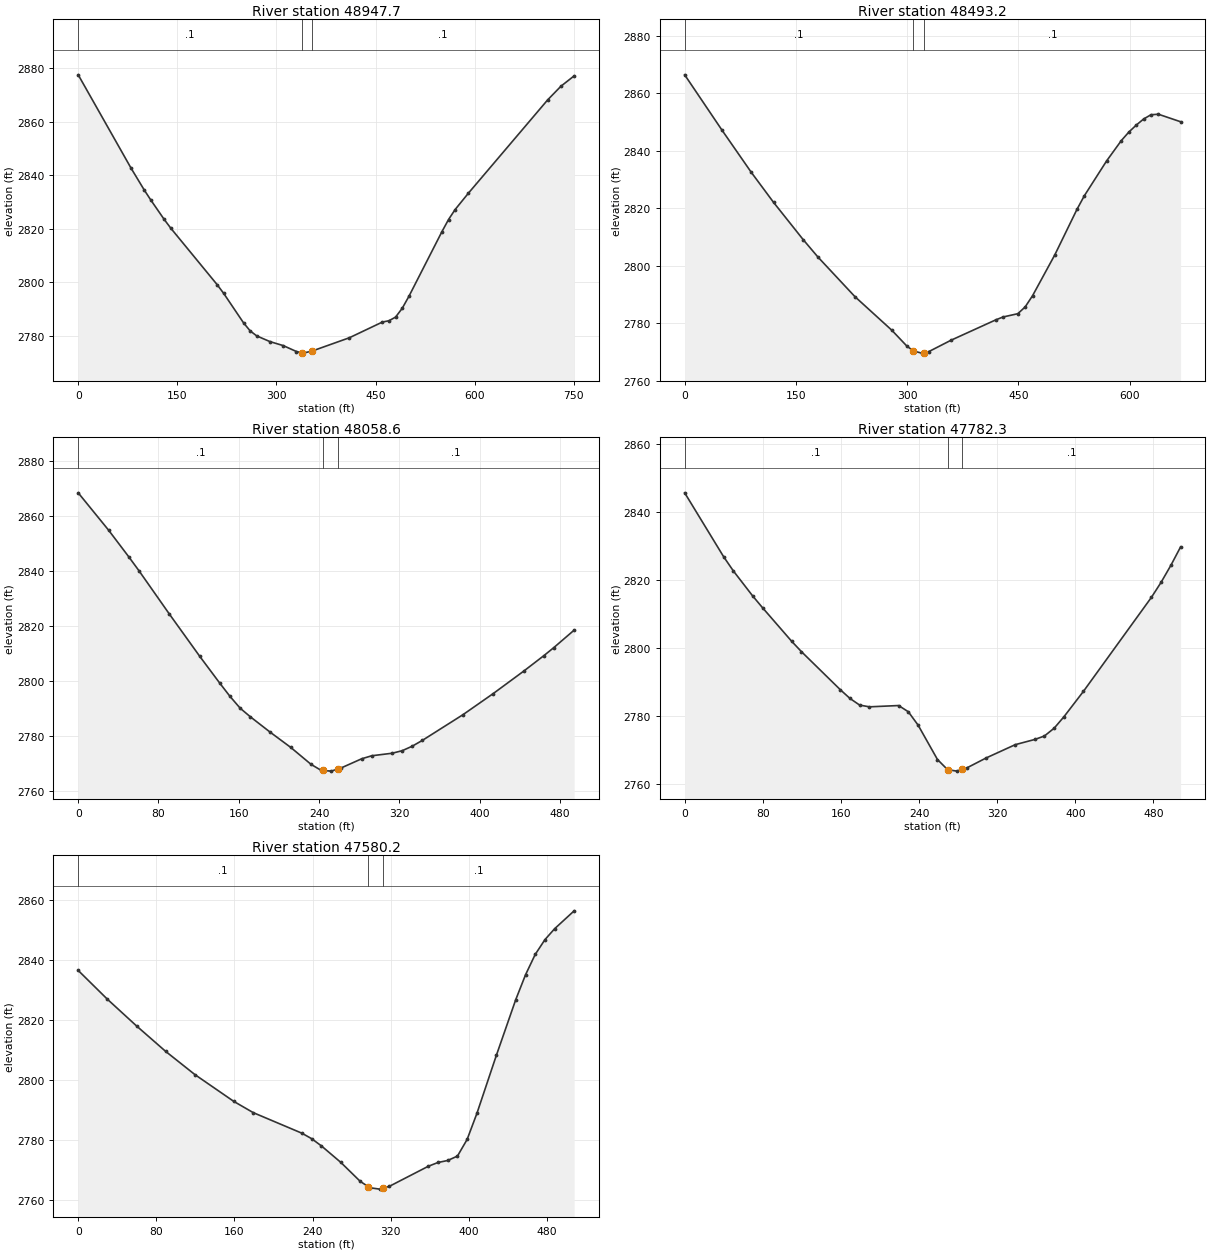
Type RM Length L Ch R = 1 ,48947.7 ,454.1,454.5,455
XS GIS Cut Line= 2
     2087233.337      364032.553     2087485.551      364739.282
#Sta/Elev= 30
       0 2877.63      80 2842.66     100 2834.46   110.1 2830.65   130.1 2823.48
   140.1 2820.19   210.1 2799.09   220.1 2795.79   250.1 2784.77   260.1 2781.76
   270.1 2779.86   290.2 2777.72   310.2 2776.23   330.2 2774.01   338.9 2773.49
   340.2 2773.41   353.9 2774.19   410.2 2779.16   460.2 2785.04   470.2 2785.54
   480.2  2786.9   490.2 2790.18   500.3 2794.64   550.3 2818.88   560.3 2823.43
   570.3 2827.18   590.3 2833.28   710.4 2868.27   730.4 2873.36   750.4 2877.24
#Mann= 3 , 0 , 0
       0      .1       0   338.9    .045       0   353.9      .1       0
Bank Sta=338.9,353.9
XS Rating Curve= 0 ,0
Exp/Cntr=0.3,0.1

Type RM Length L Ch R = 1 ,48493.2 ,435.1,434.6,434.1
XS GIS Cut Line= 2
     2086852.653      364281.266     2087077.481      364911.255
#Sta/Elev= 30
       0 2866.49    49.9  2847.4    89.8 2832.57   119.8 2822.13   159.7 2809.18
   179.7 2803.09   229.6  2789.3   279.5 2777.58   299.5 2772.14   308.2 2770.44
   319.5 2769.64   323.2 2769.85   329.5  2770.2   359.4 2774.15   419.3 2781.18
   429.3 2782.21   449.3 2783.36   459.2 2785.71   469.2 2789.62   499.2 2803.83
   529.1 2819.67   539.1 2824.43   569.1 2836.54     589 2843.63     599 2846.55
     609 2848.98     619 2851.12     629 2852.61     639 2852.77   668.9 2850.16
#Mann= 3 , 0 , 0
       0      .1       0   308.2    .045       0   323.2      .1       0
Bank Sta=308.2,323.2
XS Rating Curve= 0 ,0
Exp/Cntr=0.3,0.1

Type RM Length L Ch R = 1 ,48058.6 ,270.9,276.3,281.7
XS GIS Cut Line= 2
      2086497.04      364537.629      2086663.15      365003.088
#Sta/Elev= 30
       0 2868.35    30.3 2854.76    50.4 2845.07    60.5 2840.04    90.8 2824.28
     121 2808.94   141.2 2799.07   151.3  2794.3   161.4 2790.02   171.5 2786.91
   191.6 2781.22   211.8 2775.76     232 2769.61   242.1 2767.42   243.5 2767.38
   252.2 2767.14   258.5 2767.89   262.2 2768.33   282.4 2771.62   292.5 2772.73
   312.7 2773.64   322.8 2774.56   332.8  2776.2   342.9 2778.31   383.3 2787.64
   413.5 2795.33   443.8 2803.47     464 2809.13     474 2812.08   494.2 2818.42
#Mann= 3 , 0 , 0
       0      .1       0   243.5    .045       0   258.5      .1       0
Bank Sta=243.5,258.5
XS Rating Curve= 0 ,0
Exp/Cntr=0.3,0.1

Type RM Length L Ch R = 1 ,47782.3 ,202.1,202.1,202.1
XS GIS Cut Line= 2
     2086292.119      364590.696     2086345.284      365095.766
#Sta/Elev= 30
       0 2845.76    39.8 2827.01    49.8 2822.81    69.7 2815.41    79.7 2811.98
   109.5 2802.12   119.5 2799.07   159.3 2787.88   169.3 2785.28   179.2 2783.33
   189.2 2782.82   219.1  2783.2     229 2781.38     239 2777.46   258.9 2767.32
   269.3 2764.33   278.8 2763.91   284.3 2764.42   288.8 2764.83   308.7 2767.78
   338.6  2771.7   358.5 2773.22   368.4 2774.24   378.4 2776.54   388.4  2779.9
   408.3 2787.34     478 2815.02   487.9 2819.44   497.9 2824.42   507.9 2829.87
#Mann= 3 , 0 , 0
       0      .1       0   269.3    .045       0   284.3      .1       0
Bank Sta=269.3,284.3
XS Rating Curve= 0 ,0
Exp/Cntr=0.3,0.1

Type RM Length L Ch R = 1 ,47580.2 ,200,200,200
XS GIS Cut Line= 2
     2086093.218      364611.633     2086146.383      365116.703
#Sta/Elev= 30
       0 2836.42    29.9 2826.84    59.8 2817.94    89.6 2809.48   119.5 2801.77
   159.3 2792.86   179.2 2789.12     229 2782.28     239 2780.46     249 2778.06
   268.9 2772.57   288.8 2766.25   296.8 2764.53   298.7 2764.12   308.7 2763.66
   311.8 2763.95   318.7  2764.6   358.5 2771.26   368.4 2772.52   378.4 2773.19
   388.4 2774.66   398.3  2780.2   408.3 2788.85   428.2 2808.14   448.1 2826.72
   458.1 2834.97     468 2841.74     478 2846.68   487.9  2850.3   507.9 2856.26
#Mann= 3 , 0 , 0
       0      .1       0   296.8    .045       0   311.8      .1       0
Bank Sta=296.8,311.8
XS Rating Curve= 0 ,0
Exp/Cntr=0.3,0.1