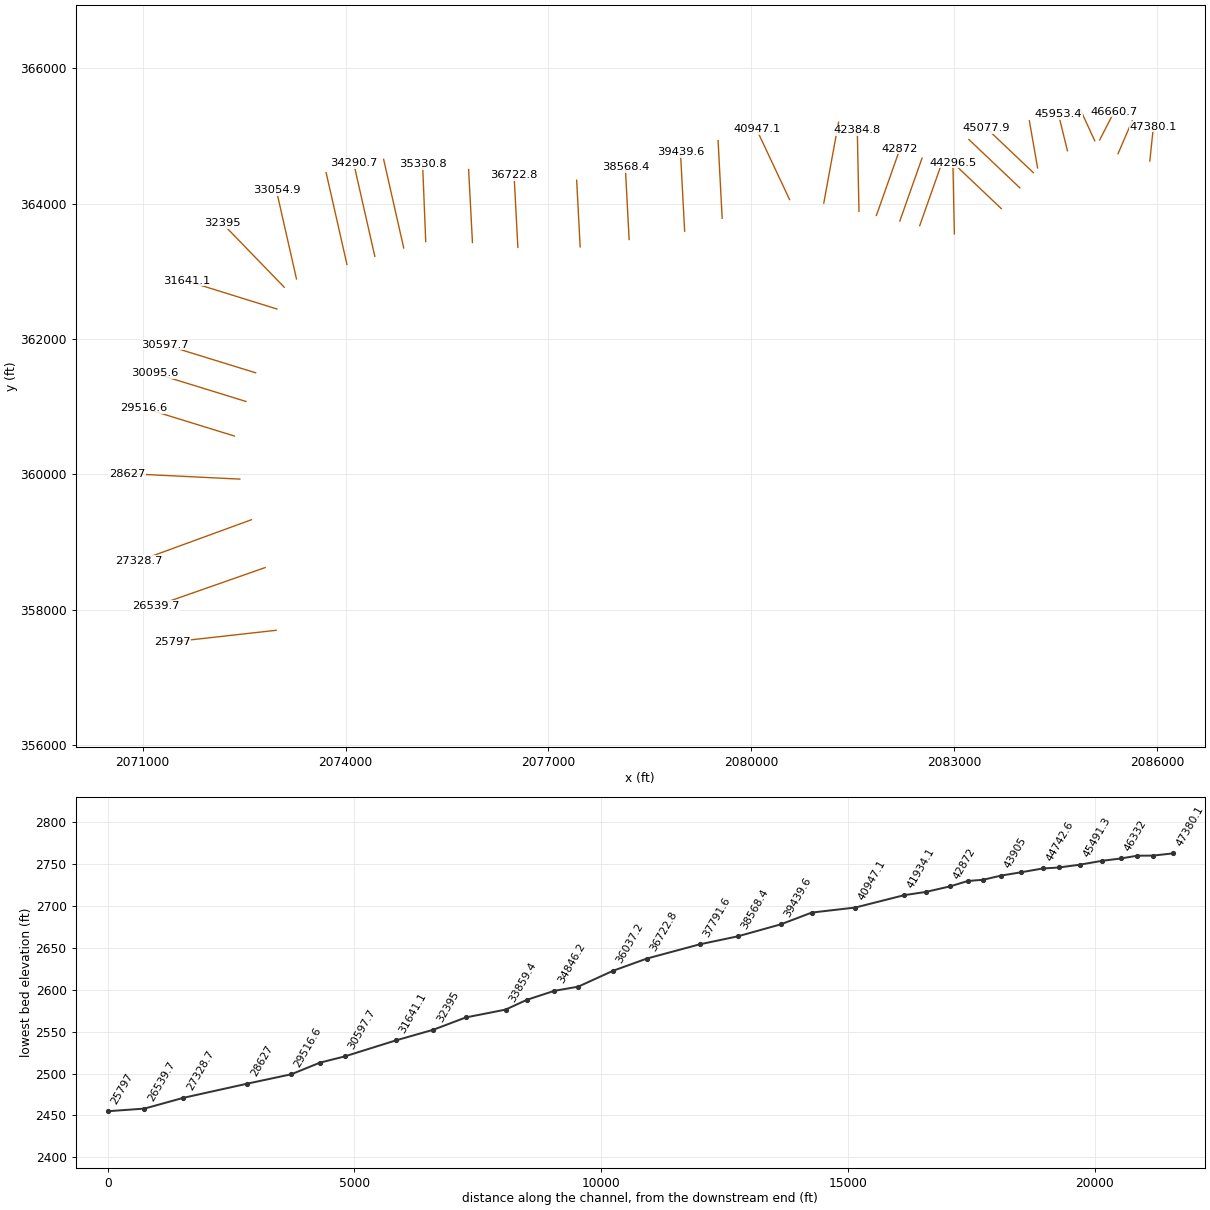
HEC-RAS study LittleClCk.prj: LittleClCk

--- LittleClCk.g01 (geometry) --- (continued)

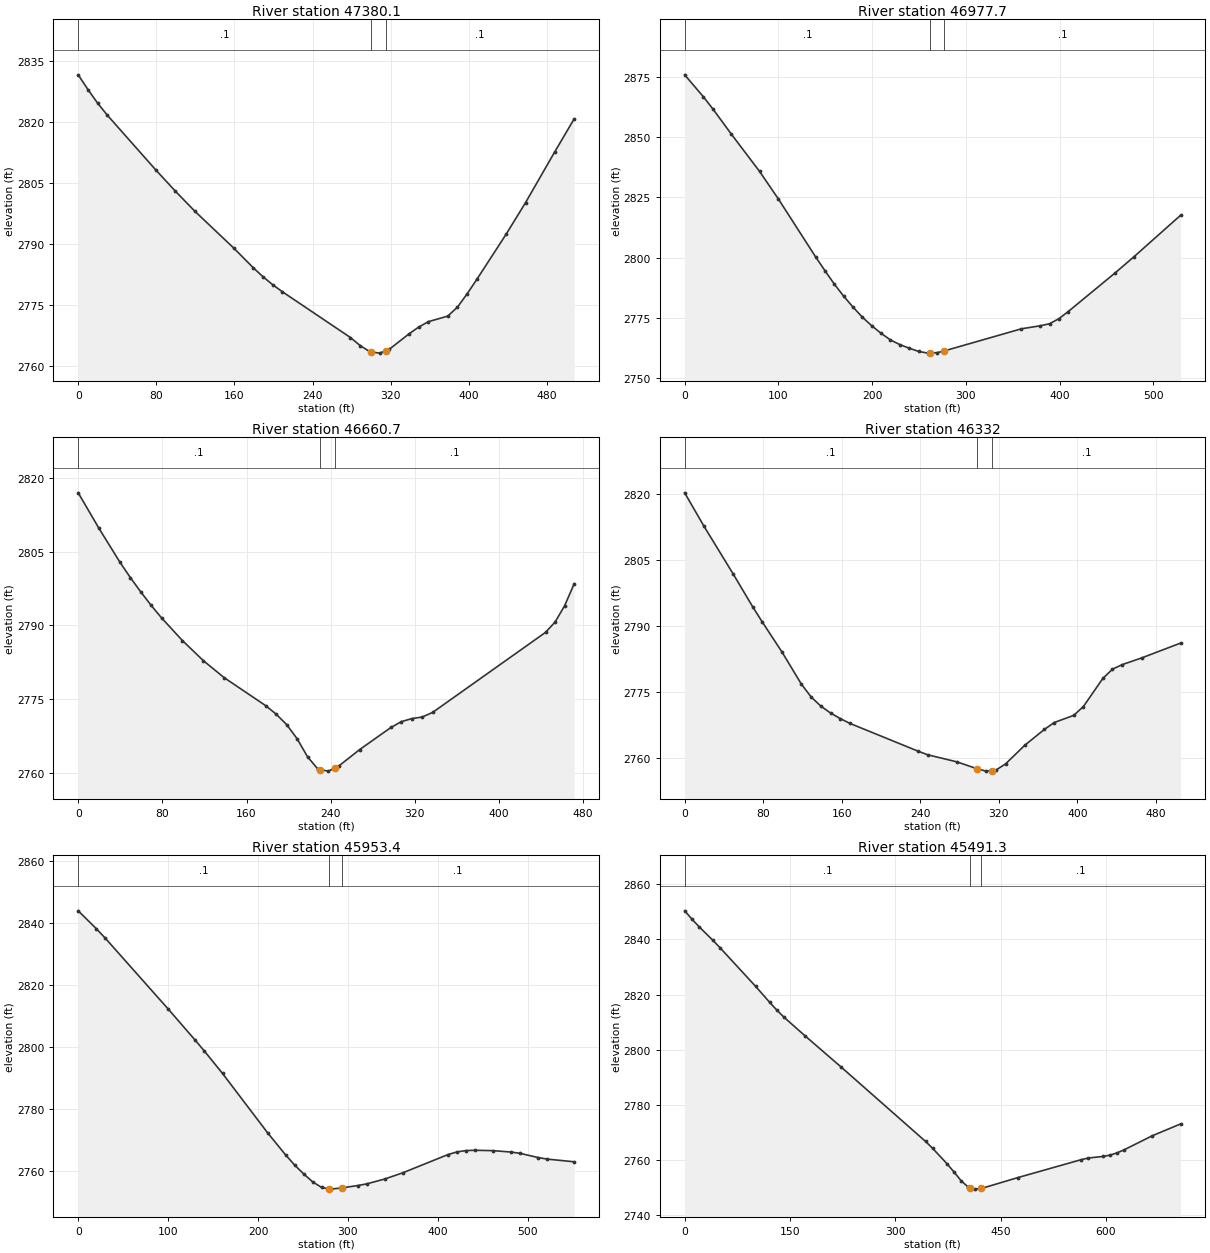
Type RM Length L Ch R = 1 ,47380.1 ,409.1,402.3,395.5
XS GIS Cut Line= 2
     2085894.317       364632.57     2085947.482       365137.64
#Sta/Elev= 30
       0 2831.56      10 2827.93    19.9 2824.58    29.9  2821.6    79.7 2808.08
    99.6  2802.9   119.5 2797.97   159.3 2788.91   179.2 2784.09   189.2 2781.86
   199.2 2779.89   209.1 2778.16   278.8 2766.89   288.8  2764.9   298.7  2763.4
     300 2763.35   308.7 2763.05     315 2763.66   318.7 2764.02   338.6 2767.76
   348.5 2769.43   358.5 2770.79   378.4 2772.16   388.4 2774.37   398.3 2777.65
   408.3 2781.23   438.2 2792.31   458.1 2800.09   487.9 2812.55   507.9 2820.71
#Mann= 3 , 0 , 0
       0      .1       0     300    .045       0     315      .1       0
Bank Sta=300,315
XS Rating Curve= 0 ,0
Exp/Cntr=0.3,0.1

Type RM Length L Ch R = 1 ,46977.7 ,318.7,317.1,315.5
XS GIS Cut Line= 2
     2085424.541      364740.151     2085633.495      365226.298
#Sta/Elev= 30
       0 2875.86      20 2866.74      30 2861.75    49.9  2851.2    79.9  2835.8
    99.8 2824.47   139.8 2800.29   149.8 2794.54   159.7 2789.05   169.7 2784.01
   179.7 2779.47   189.7 2775.29   199.7 2771.74   209.7 2768.59   219.6 2765.88
   229.6 2763.95   239.6 2762.46   249.6 2761.12   259.6 2760.41   261.8 2760.46
   269.6 2760.62   276.8 2761.31   359.4 2770.51   379.4 2771.75   389.4 2772.61
   399.4 2774.71   409.3 2777.67   459.3 2793.68   479.2 2800.32   529.2 2817.61
#Mann= 3 , 0 , 0
       0      .1       0   261.8    .045       0   276.8      .1       0
Bank Sta=261.8,276.8
XS Rating Curve= 0 ,0
Exp/Cntr=0.3,0.1

Type RM Length L Ch R = 1 ,46660.7 ,308.1,328.7,349.3
XS GIS Cut Line= 3
     2085152.831      364943.516     2085347.964      365322.378
     2085368.741      365362.718
#Sta/Elev= 30
       0 2816.95    19.8  2809.7    39.6 2802.86    49.6  2799.7    59.5 2796.79
    69.4 2794.04    79.3 2791.49    99.1 2786.89   118.9 2782.82   138.8 2779.34
   178.4 2773.63   188.3  2771.9   198.2 2769.79   208.1 2766.92     218 2763.26
     228 2760.71   229.6 2760.65   237.9 2760.33   244.6 2761.04   247.8 2761.38
   267.6 2764.72   297.3 2769.21   307.2  2770.4   317.1 2771.01     327 2771.34
     337 2772.28   444.3 2788.56   453.4 2790.67   462.5    2794   471.5 2798.44
#Mann= 3 , 0 , 0
       0      .1       0   229.6    .045       0   244.6      .1       0
Bank Sta=229.6,244.6
XS Rating Curve= 0 ,0
Exp/Cntr=0.3,0.1

Type RM Length L Ch R = 1 ,46332   ,382.9,378.6,374.3
XS GIS Cut Line= 2
     2085080.162      364930.842      2084868.68      365389.642
#Sta/Elev= 30
       0 2820.26    19.8 2812.62    49.5 2801.79    69.3 2794.36    79.2 2790.86
    99.1  2784.1   118.9 2776.78   128.8 2773.88   138.7 2771.79   148.6 2770.23
   158.5 2768.96   168.4 2767.86   237.7 2761.56   247.6 2760.73   277.4 2759.12
     298 2757.55   307.1 2757.02     313 2757.15     317 2757.24   326.9 2758.67
   346.7 2762.95   366.5 2766.51   376.4 2768.06   396.2 2769.68   406.1 2771.68
     426 2778.09   435.8 2780.19   445.8 2781.23   465.6 2782.75   505.2 2786.12
#Mann= 3 , 0 , 0
       0      .1       0     298    .045       0     313      .1       0
Bank Sta=298,313
XS Rating Curve= 0 ,0
Exp/Cntr=0.3,0.1

Type RM Length L Ch R = 1 ,45953.4 ,463.6,462.1,460.6
XS GIS Cut Line= 2
      2084675.78      364783.794     2084544.457      365319.589
#Sta/Elev= 30
       0 2843.93    20.1 2838.19    30.1 2835.12   100.3 2812.22   130.4 2802.15
   140.4 2798.72   160.5 2791.53   210.6 2772.42   230.7 2765.27   240.7 2762.02
   250.8 2759.14   260.8 2756.59   270.8 2754.78   278.6 2754.37   280.8 2754.25
   293.6 2754.66   310.9 2755.41     321 2755.95     341 2757.52   361.1 2759.52
   411.2 2765.38   421.3 2766.24   431.3 2766.68   441.3 2766.77   461.4 2766.65
   481.4  2766.2   491.5 2765.78   511.5 2764.43   521.6 2763.93   551.6 2763.06
#Mann= 3 , 0 , 0
       0      .1       0   278.6    .045       0   293.6      .1       0
Bank Sta=278.6,293.6
XS Rating Curve= 0 ,0
Exp/Cntr=0.3,0.1

Type RM Length L Ch R = 1 ,45491.3 ,397.1,413.4,429.7
XS GIS Cut Line= 2
     2084234.599      364530.617     2084113.016      365226.369
#Sta/Elev= 30
       0 2850.34    10.1 2847.41    20.2 2844.66    40.4 2839.61    50.4 2836.96
   100.9 2823.02   121.1 2817.18   131.2 2814.39   141.3 2811.84   171.5 2805.04
     222 2793.94   343.1  2766.8   353.2 2764.29   373.3 2758.81   383.4  2755.8
   393.5 2752.62   403.6 2750.31   406.4 2750.09   413.7 2749.53   421.4 2749.78
   423.8 2749.86   474.2 2753.69     565 2760.22   575.1 2760.81   595.3 2761.36
   605.4 2761.82   615.5 2762.64   625.6 2763.74   665.9 2768.86   706.3 2773.15
#Mann= 3 , 0 , 0
       0      .1       0   406.4    .045       0   421.4      .1       0
Bank Sta=406.4,421.4
XS Rating Curve= 0 ,0
Exp/Cntr=0.3,0.1

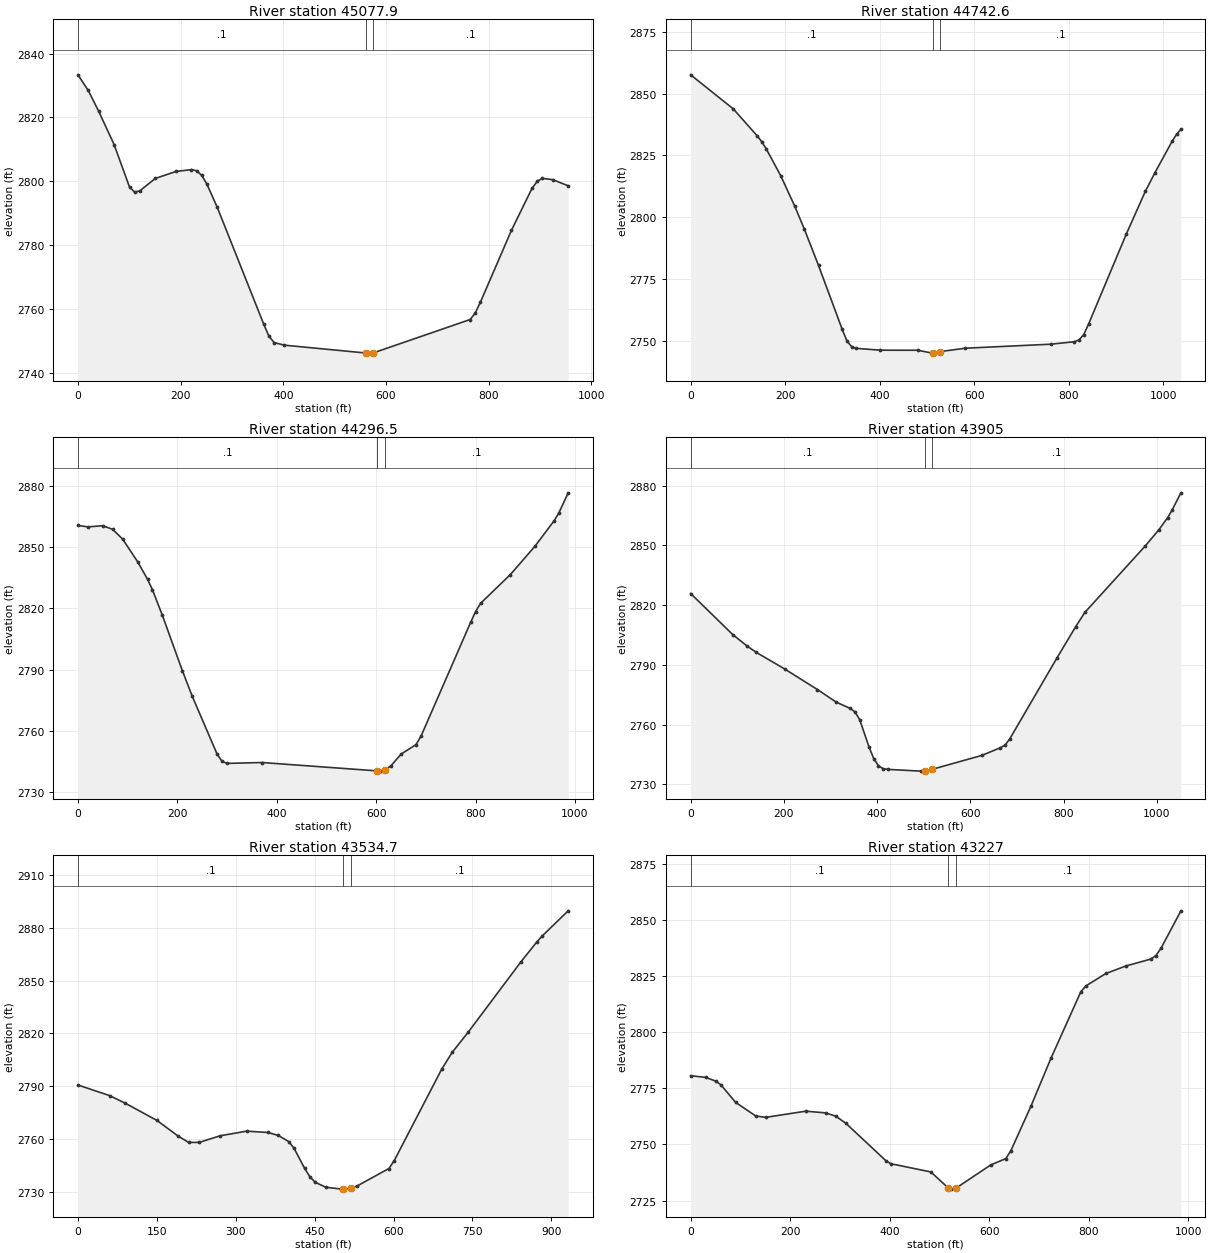
Type RM Length L Ch R = 1 ,45077.9 ,336.3,335.1,333.8
XS GIS Cut Line= 2
     2084171.588      364459.942     2083478.667      365116.665
#Sta/Elev= 30
       0 2833.34    20.1 2828.44    40.2 2822.01    70.4 2811.53   100.5  2798.2
   110.5 2796.62   120.6 2797.05   150.7 2800.91   190.9 2803.09   221.1 2803.68
   231.1 2803.31   241.2 2801.86   251.2 2799.11   271.3 2791.88   361.8  2755.3
   371.8 2751.59   381.9 2749.56     402 2748.73   560.5 2746.28   562.8 2746.24
   575.5 2746.33   763.8 2756.76   773.8 2758.83   783.8  2762.2   844.1 2784.64
   884.3 2797.82   894.4 2800.01   904.4 2800.93   924.5 2800.53   954.7 2798.62
#Mann= 3 , 0 , 0
       0      .1       0   560.5    .045       0   575.5      .1       0
Bank Sta=560.5,575.5
XS Rating Curve= 0 ,0
Exp/Cntr=0.3,0.1

Type RM Length L Ch R = 1 ,44742.6 ,446.5,446.1,445.7
XS GIS Cut Line= 3
     2083971.851      364235.913     2083258.974       364911.55
      2083218.88       364949.55
#Sta/Elev= 30
       0 2857.59    90.2 2843.82   140.3 2833.02   150.3 2830.58   160.4 2827.48
   190.4 2816.87   220.5 2804.36   240.5 2795.23   270.6 2780.48   320.7 2754.65
   330.7 2749.94   340.8 2747.63   350.8 2746.96   400.9 2746.22   481.1 2746.19
   511.1 2745.03   513.4 2745.09   528.4 2745.67   581.3 2747.02   761.7 2748.64
   811.8 2749.63   821.8 2750.35   831.8 2752.53   841.9 2756.72     922 2793.25
   962.1 2810.46   982.2 2817.93    1019 2830.78  1028.2 2833.52  1037.4 2835.52
#Mann= 3 , 0 , 0
       0      .1       0   513.4    .045       0   528.4      .1       0
Bank Sta=513.4,528.4
XS Rating Curve= 0 ,0
Exp/Cntr=0.3,0.1

Type RM Length L Ch R = 1 ,44296.5 ,409.8,391.5,373.2
XS GIS Cut Line= 3
      2083697.98      363928.733     2083022.869      364568.576
     2082982.087      364607.228
#Sta/Elev= 30
       0 2860.47      20 2859.78      50 2860.34      70 2858.56      90 2853.77
     120  2842.8     140 2834.19     150 2828.99     170 2816.48     210 2789.54
     230 2776.98     280 2748.71     290 2745.18     300 2744.18   370.1 2744.61
   602.4 2740.51   610.1  2740.4   617.4 2740.74   630.1  2743.1   650.1 2748.72
   680.1 2753.35   690.1 2757.43   790.1 2813.14   800.1 2818.39   810.1 2822.44
   870.1 2836.49   920.2 2850.52   958.2 2862.85   967.6 2866.63   986.3 2876.42
#Mann= 3 , 0 , 0
       0      .1       0   602.4    .045       0   617.4      .1       0
Bank Sta=602.4,617.4
XS Rating Curve= 0 ,0
Exp/Cntr=0.3,0.1

Type RM Length L Ch R = 1 ,43905   ,378.8,370.4,362.1
XS GIS Cut Line= 3
     2083003.989      363555.927     2082984.066       364512.21
     2082982.087      364607.228
#Sta/Elev= 30
       0 2825.83    90.6 2805.14   120.8 2799.49     141 2796.22   201.4 2787.96
   271.8  2777.6   312.1 2771.28   342.3 2768.08   352.4 2766.36   362.5  2762.5
   382.6 2748.74   392.7 2742.88   402.7 2739.27   412.8 2737.81   422.9 2737.47
   493.4 2736.59     502  2736.7     517 2737.44   624.2 2744.46   664.5 2748.35
   674.6 2749.71   684.6 2752.85   785.3 2793.32   825.6 2809.08   845.7 2816.39
   975.5 2849.85    1004 2857.79    1023 2863.91  1032.5 2867.71  1051.5 2876.42
#Mann= 3 , 0 , 0
       0      .1       0     502    .045       0     517      .1       0
Bank Sta=502,517
XS Rating Curve= 0 ,0
Exp/Cntr=0.3,0.1

Type RM Length L Ch R = 1 ,43534.7 ,307.9,307.6,308
XS GIS Cut Line= 2
     2082491.214      363676.415     2082801.862      364555.238
#Sta/Elev= 30
       0 2790.67    60.1 2784.66    90.2 2780.29   150.3 2770.53   190.4 2761.66
   210.5 2758.05   230.5 2758.06   270.6 2761.83   320.7 2764.45   360.8  2763.7
   380.9 2762.03   400.9  2758.5   410.9 2754.73     431 2743.31     441 2738.53
     451 2735.43   471.1 2732.62   501.1 2731.52   504.3 2731.52   519.3 2732.02
   531.2 2733.38   591.3 2743.23   601.4 2747.73   691.6 2799.65   711.6  2809.2
   741.7 2820.55   841.9 2860.49     872 2871.75     882 2875.11   932.1  2889.6
#Mann= 3 , 0 , 0
       0      .1       0   504.3    .045       0   519.3      .1       0
Bank Sta=504.3,519.3
XS Rating Curve= 0 ,0
Exp/Cntr=0.3,0.1

Type RM Length L Ch R = 1 ,43227   ,413.3,355,399.5
XS GIS Cut Line= 2
     2082197.424      363745.448     2082525.709      364674.165
#Sta/Elev= 30
       0 2780.63    30.2 2779.89    50.3 2778.24    60.3 2776.69    90.5 2768.72
   130.7  2762.7   150.8 2762.07   231.2 2764.83   271.4 2764.07   291.5  2762.6
   311.6 2759.49     392 2742.81     402 2741.43   482.5 2737.75   517.2 2730.71
   522.7 2730.09   532.2 2730.39   603.1  2740.9   633.2 2743.69   643.3 2747.19
   683.5 2766.94   723.7 2788.31     784 2818.09   794.1 2820.64   834.3 2826.19
   874.5 2829.55   924.7 2832.63   934.8  2834.2   944.8 2837.36     985 2854.12
#Mann= 3 , 0 , 0
       0      .1       0   517.2    .045       0   532.2      .1       0
Bank Sta=517.2,532.2
XS Rating Curve= 0 ,0
Exp/Cntr=0.3,0.1

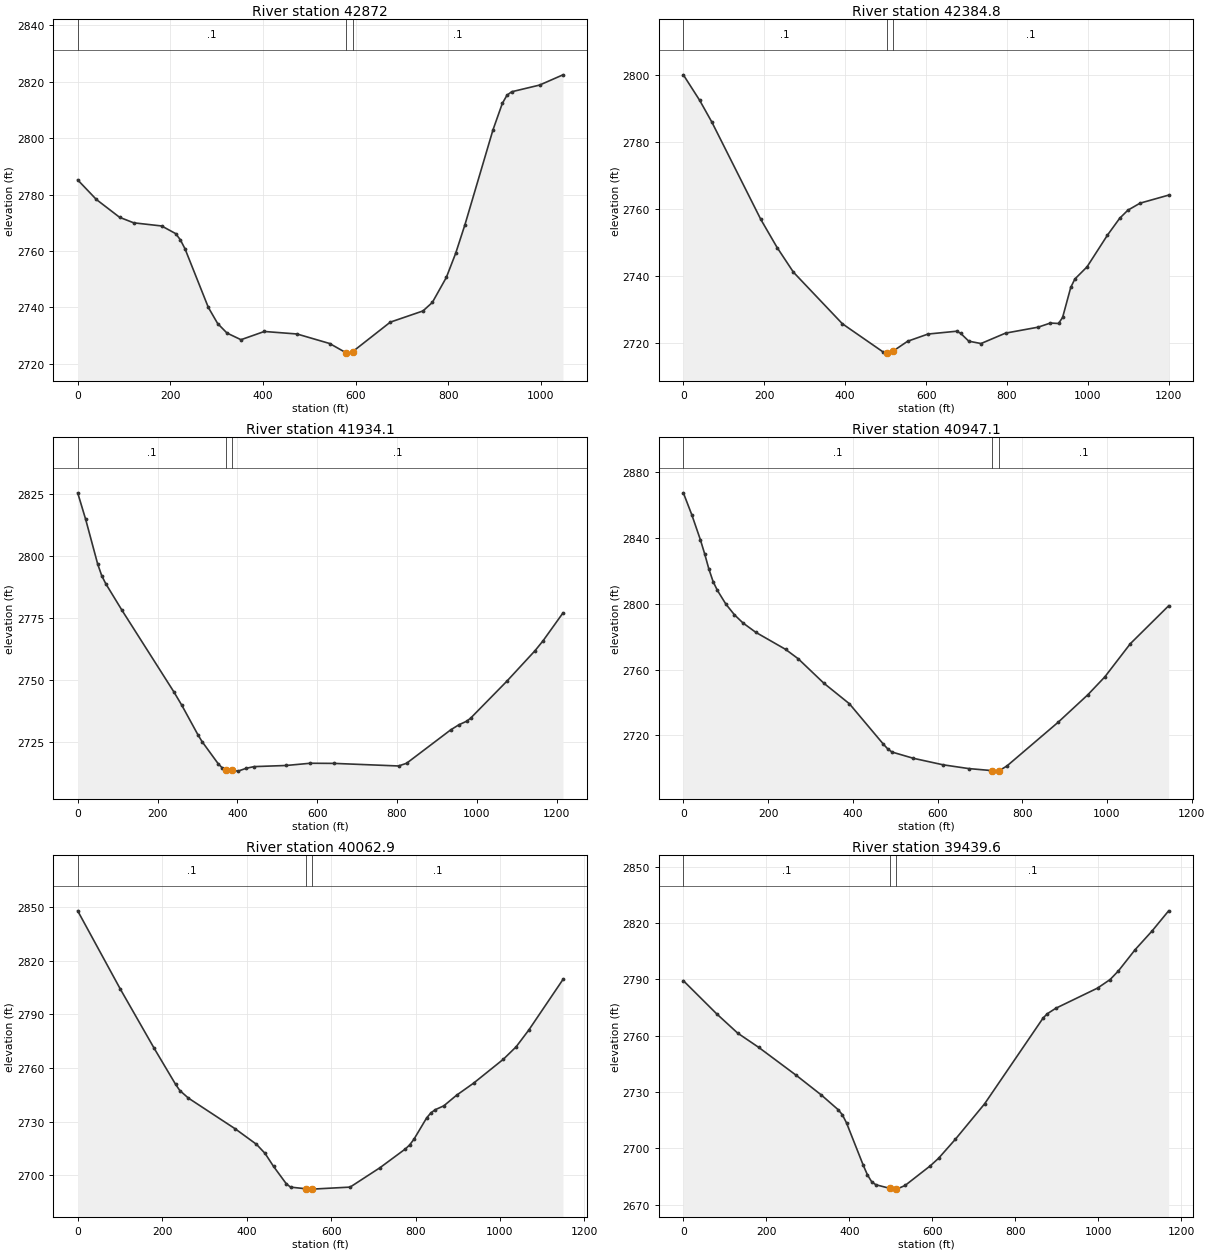
Type RM Length L Ch R = 1 ,42872   ,479.1,487.2,495.3
XS GIS Cut Line= 2
     2081850.694       363826.92     2082199.794      364814.523
#Sta/Elev= 30
       0 2785.19    40.3 2778.24    90.6  2771.9   120.9 2769.96   181.3 2768.84
   211.5 2766.13   221.6 2763.94   231.7 2760.73     282 2739.96   302.2 2734.22
   322.3 2730.86   352.5  2728.5   402.9 2731.42   473.4 2730.53   543.9 2727.15
   578.8 2723.91   584.2 2723.74   593.8  2724.3   674.8 2734.73   745.3  2738.7
   765.5 2741.71   795.7 2750.57   815.8  2759.1     836 2769.34   896.4 2802.91
   916.6 2812.31   926.6 2815.21   936.7 2816.44   997.1 2818.82  1047.5 2822.45
#Mann= 3 , 0 , 0
       0      .1       0   578.8    .045       0   593.8      .1       0
Bank Sta=578.8,593.8
XS Rating Curve= 0 ,0
Exp/Cntr=0.3,0.1

Type RM Length L Ch R = 1 ,42384.8 ,455.2,450.5,443.9
XS GIS Cut Line= 2
     2081593.165      363887.432     2081568.183      365086.531
#Sta/Elev= 30
       0 2800.09    40.3 2792.49    70.6 2785.96   191.5 2756.96   231.8 2748.58
   272.1 2741.23   393.1 2725.85   493.8 2717.44   503.6 2717.11   503.9  2717.1
   518.6 2717.73   554.3 2720.64   604.7 2722.79   675.3 2723.63   685.4    2723
   705.5 2720.66   735.7 2719.96   796.2 2723.06   876.8 2724.84   907.1 2726.07
   927.2 2725.94   937.3 2727.73   957.5 2736.71   967.6 2739.19   997.8 2742.84
  1048.2 2752.29  1078.4 2757.31  1098.6 2759.72  1128.8 2761.82  1199.4 2764.22
#Mann= 3 , 0 , 0
       0      .1       0   503.6    .045       0   518.6      .1       0
#XS Ineff= 2 , 0
                          671.74         2723.53
Permanent Ineff=
       F       F
Bank Sta=503.6,518.6
XS Rating Curve= 0 ,0
Exp/Cntr=0.3,0.1

Type RM Length L Ch R = 1 ,41934.1 ,971.2,986.9,1004.6
XS GIS Cut Line= 2
     2081072.515      364009.771     2081291.397       365205.73
#Sta/Elev= 30
       0 2825.43    20.1 2814.67    50.2 2796.63    60.3 2791.97    70.3 2788.77
   110.5 2778.16   241.2 2745.04   261.2  2739.6   301.4 2727.74   311.5 2725.06
   351.7 2716.17   361.7 2714.48   371.4 2713.67   386.4  2713.5   401.9 2713.11
     422 2714.25   442.1 2714.93   522.5 2715.39   582.8 2716.29   643.1 2716.23
   803.8 2715.19     824 2716.28   934.5 2729.76   954.6 2731.77   974.7 2733.27
   984.7 2734.53  1075.2  2749.4  1145.5 2761.67  1165.6 2765.65  1215.8 2776.95
#Mann= 3 , 0 , 0
       0      .1       0   371.4    .045       0   386.4      .1       0
Bank Sta=371.4,386.4
XS Rating Curve= 0 ,0
Exp/Cntr=0.3,0.1

Type RM Length L Ch R = 1 ,40947.1 ,892.8,884.2,875.5
XS GIS Cut Line= 2
     2080566.672      364062.233     2080079.099      365098.797
#Sta/Elev= 30
       0 2867.24    20.1 2853.81    40.2 2838.77    50.2 2830.32    60.3 2820.96
    70.3 2813.34    80.4 2808.03   100.5 2799.67   120.6 2793.24   140.7 2788.29
   170.8 2782.63   241.2 2772.27   271.3 2766.52   331.6 2751.74   391.9 2739.26
   472.3 2714.68   482.3  2711.9   492.4 2709.96   542.6 2706.18     613 2702.21
   673.2 2699.93   729.1 2698.67   743.6 2698.37   744.1 2698.43   763.7 2701.48
   884.2 2727.92   954.6 2744.67   994.8 2755.54  1055.1  2775.7  1145.5 2798.69
#Mann= 3 , 0 , 0
       0      .1       0   729.1    .045       0   744.1      .1       0
Bank Sta=729.1,744.1
XS Rating Curve= 0 ,0
Exp/Cntr=0.3,0.1

Type RM Length L Ch R = 1 ,40062.9 ,625.6,623.5,621.3
XS GIS Cut Line= 2
     2079569.769      363786.494     2079509.374         364934.
#Sta/Elev= 30
       0 2847.93   100.8 2804.26   181.4 2770.96   231.8 2750.94   241.9 2747.45
   262.1 2743.24     373 2726.05   423.4 2717.38   443.5 2712.36   463.7 2705.07
   493.9 2695.34     504 2693.45     540 2692.54   554.4 2692.33     555 2692.33
   645.1 2693.46   715.7 2704.29   776.1 2714.83   786.2 2717.08   796.3 2720.25
   826.5 2732.23   836.6 2735.01   846.7 2736.75   866.9 2738.89   897.1 2744.82
   937.4 2751.57    1008 2764.96  1038.2  2771.9  1068.5 2781.39  1149.1 2809.56
#Mann= 3 , 0 , 0
       0      .1       0     540    .045       0     555      .1       0
Bank Sta=540,555
XS Rating Curve= 0 ,0
Exp/Cntr=0.3,0.1

Type RM Length L Ch R = 1 ,39439.6 ,870.9,871.4,873.1
XS GIS Cut Line= 2
      2079014.56      363595.809     2078953.093      364763.684
#Sta/Elev= 30
       0 2789.36    80.6 2771.64   131.1 2761.41   181.5 2753.86   272.2 2738.93
   332.7 2728.44     373 2720.66   383.1 2717.98   393.2 2713.62   433.5 2691.08
   443.6 2685.95   453.7 2682.32   463.8 2680.67   497.2 2678.77   512.2 2678.36
   514.2 2678.33   534.3 2680.27   594.8 2690.69     615 2694.75   655.3 2704.83
   725.9 2723.74     867 2769.48   877.1 2771.74   897.3 2774.64   998.1 2785.41
  1028.4 2789.96  1048.5 2794.58  1088.8 2805.89  1129.2 2815.74  1169.5 2826.57
#Mann= 3 , 0 , 0
       0      .1       0   497.2    .045       0   512.2      .1       0
Bank Sta=497.2,512.2
XS Rating Curve= 0 ,0
Exp/Cntr=0.3,0.1

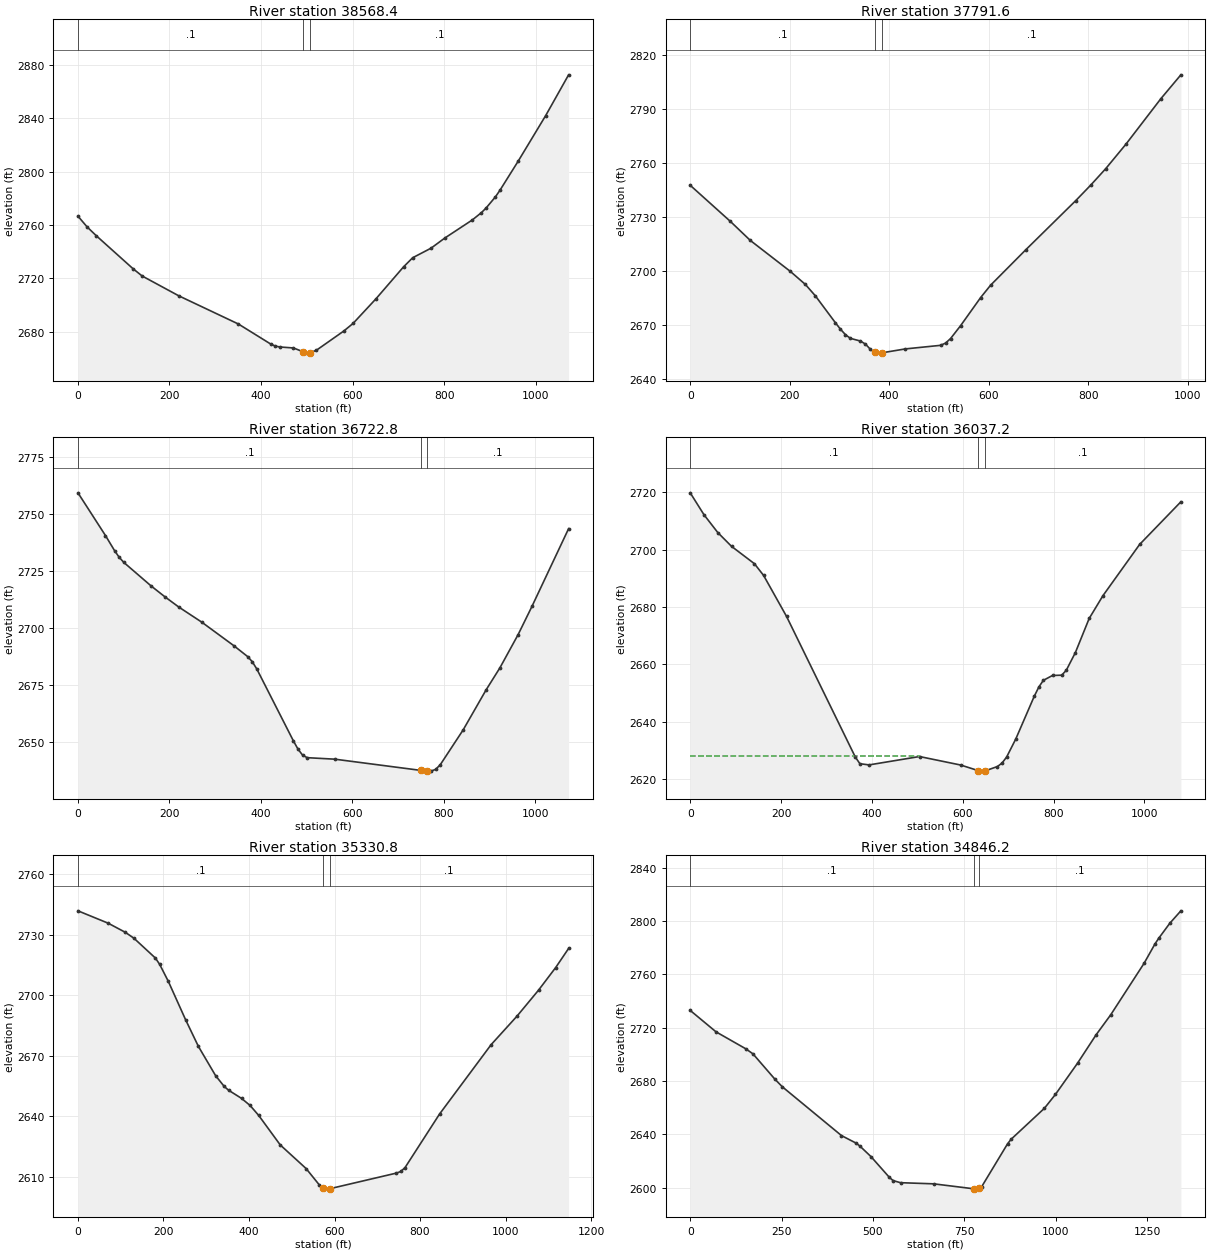
Type RM Length L Ch R = 1 ,38568.4 ,775.7,776.3,776.9
XS GIS Cut Line= 2
     2078193.744      363472.418     2078137.395      364543.045
#Sta/Elev= 30
       0  2766.7      20 2758.63    40.1 2752.01   120.2 2727.33   140.3 2721.82
   220.4 2706.95   350.7  2685.8   420.8 2670.88   430.8 2669.32   440.9 2668.61
   470.9 2667.86   491.8 2665.05     501 2663.99   506.8 2664.23     521 2666.14
   581.1 2680.62   601.2 2686.29   651.3 2704.78   711.4 2728.66   731.4 2735.52
   771.5 2742.68   801.6 2750.29   861.7 2763.86   881.7 2769.37   891.8 2772.81
   911.8    2781   921.8 2785.96   961.9 2807.93    1022 2842.11  1072.1 2872.67
#Mann= 3 , 0 , 0
       0      .1       0   491.8    .045       0   506.8      .1       0
Bank Sta=491.8,506.8
XS Rating Curve= 0 ,0
Exp/Cntr=0.3,0.1

Type RM Length L Ch R = 1 ,37791.6 ,1068.2,1068.8,1069.4
XS GIS Cut Line= 2
     2077469.668       363363.57     2077417.834      364348.409
#Sta/Elev= 30
       0 2747.59    80.5 2727.58   120.8 2716.95   201.3 2699.74   231.5  2692.5
   251.6 2686.16   291.8 2671.24   301.9 2667.68     312 2664.61     322 2662.56
   342.2 2661.06   352.2 2659.38   362.3 2656.43     371 2654.72   382.4 2654.36
     386 2654.57   432.7 2656.71   503.2 2658.69   513.2 2659.94   523.3 2662.46
   543.4 2669.59   583.7 2685.21   603.8 2692.11   674.2  2711.7   774.9 2739.07
   805.1 2747.71   835.2 2756.84   875.5 2770.33     946  2795.7   986.2 2808.94
#Mann= 3 , 0 , 0
       0      .1       0     371    .045       0     386      .1       0
Bank Sta=371,386
XS Rating Curve= 0 ,0
Exp/Cntr=0.3,0.1

Type RM Length L Ch R = 1 ,36722.8 ,686.4,685.7,685.1
XS GIS Cut Line= 2
     2076548.407      363354.876     2076492.012      364426.388
#Sta/Elev= 30
       0 2759.12    60.2 2740.43    80.2 2733.79    90.2 2730.92   100.3 2728.68
   160.4 2718.32   190.5 2713.59   220.6 2709.15   270.8 2702.55     341 2692.24
     371 2687.51   381.1 2685.28   391.1 2682.08   471.3 2650.56   481.3 2646.98
   491.4 2644.35   501.4 2643.27   561.6 2642.62   749.4 2637.72   762.1 2637.39
   764.4  2637.4   772.2 2637.43   782.2 2638.15   792.2 2640.15   842.4 2655.43
   892.5 2672.91   922.6 2682.52   962.7 2697.15   992.8 2709.43    1073 2743.46
#Mann= 3 , 0 , 0
       0      .1       0   749.4    .045       0   764.4      .1       0
Bank Sta=749.4,764.4
XS Rating Curve= 0 ,0
Exp/Cntr=0.3,0.1

Type RM Length L Ch R = 1 ,36037.2 ,703.7,706.1,734.2
XS GIS Cut Line= 2
     2075876.704      363427.644     2075819.927      364506.398
#Sta/Elev= 30
       0 2719.86    30.3 2712.22    60.6 2706.02    90.9  2701.2   141.3 2695.14
   161.5 2691.06     212 2676.77   363.4 2627.71   373.5 2625.37   393.7 2624.95
   504.8 2627.87   595.6  2624.9   633.9 2622.97   646.1 2622.78   648.9 2622.85
   676.4 2624.39   686.5  2625.6   696.6  2627.7   716.8 2634.02   757.2 2648.82
   767.3 2652.07   777.4 2654.45   797.6 2656.15   817.8 2656.25   827.8 2657.93
     848 2664.16   878.3 2676.03   908.6 2683.98   989.4 2701.86  1080.2 2716.73
#Mann= 3 , 0 , 0
       0      .1       0   633.9    .045       0   648.9      .1       0
#XS Ineff= 2 , 0
          503.81 2627.89
Permanent Ineff=
       F       F
Bank Sta=633.9,648.9
XS Rating Curve= 0 ,0
Exp/Cntr=0.3,0.1

Type RM Length L Ch R = 1 ,35330.8 ,480.1,484.6,489
XS GIS Cut Line= 2
     2075185.607      363440.843     2075139.236      364587.432
#Sta/Elev= 30
       0 2741.88    70.5 2735.76   110.7 2731.23   130.9 2728.29   181.2 2718.43
   191.2 2715.28   211.4 2706.86   251.6 2687.91   281.8 2674.57   322.1 2660.03
   342.2 2654.72   352.3 2652.86   382.5 2648.83   402.6  2645.3   422.8 2640.34
   473.1 2625.72   533.5 2614.02   563.7 2606.08   573.9 2604.12   583.8 2603.79
   588.9 2603.99   744.9 2611.75     755 2612.54     765  2614.5   845.6 2641.03
   966.3 2675.48  1026.7  2689.6  1077.1  2702.5  1117.3 2713.75  1147.5 2723.22
#Mann= 3 , 0 , 0
       0      .1       0   573.9    .045       0   588.9      .1       0
Bank Sta=573.9,588.9
XS Rating Curve= 0 ,0
Exp/Cntr=0.3,0.1

Type RM Length L Ch R = 1 ,34846.2 ,557.7,555.5,553.4
XS GIS Cut Line= 2
     2074860.215       363346.98     2074563.226      364656.005
#Sta/Elev= 30
       0 2732.87    70.6  2716.8   151.4 2704.18   171.6 2700.31   232.1 2681.15
   252.3  2675.5   413.8 2638.97   454.2 2633.26   464.2 2631.09   494.5  2623.2
     545 2607.57   555.1 2605.19   575.3 2603.63   666.1 2602.77   775.3 2599.06
   787.2  2598.8   790.3 2599.36   797.3 2600.62     868 2632.73     878 2636.25
   968.9 2659.43   999.2 2669.88  1059.7 2693.33  1110.2 2714.52  1150.5 2729.64
  1241.4 2768.12  1271.6 2782.84  1281.7    2787    1312 2798.26  1342.3 2807.59
#Mann= 3 , 0 , 0
       0      .1       0   775.3    .045       0   790.3      .1       0
Bank Sta=775.3,790.3
XS Rating Curve= 0 ,0
Exp/Cntr=0.3,0.1

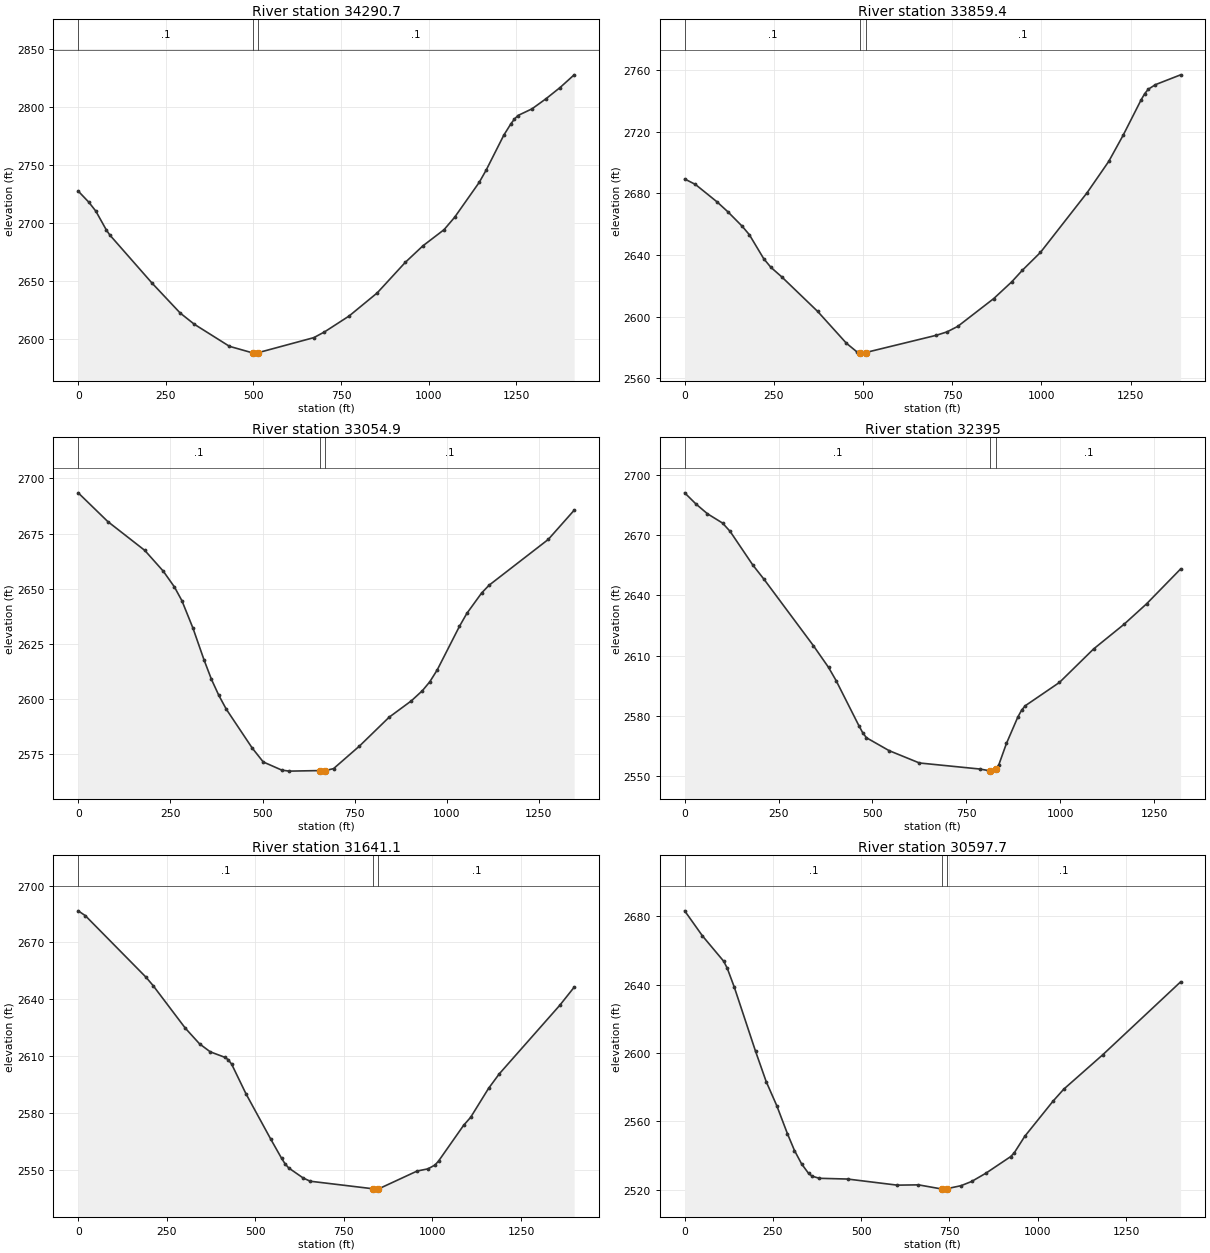
Type RM Length L Ch R = 1 ,34290.7 ,429.5,431.2,432.9
XS GIS Cut Line= 2
      2074432.57       363223.62     2074119.563      364603.244
#Sta/Elev= 30
       0 2727.59    30.1 2718.06    50.2 2710.36    80.3 2694.07    90.3 2689.71
   210.7 2648.32     291 2622.56   331.1 2612.96   431.4 2593.93   497.7 2588.26
   501.7 2588.07   512.7 2588.41   672.2 2601.42   702.3 2606.29   772.6    2620
   852.8 2639.88   933.1 2666.24   983.3 2680.45  1043.5 2694.33  1073.6 2704.97
  1143.8 2735.05  1163.8  2745.7    1214  2775.7  1234.1 2785.44  1244.1 2789.46
  1254.2 2792.62  1294.3 2798.35  1334.4 2807.08  1374.6 2816.75  1414.7 2827.67
#Mann= 3 , 0 , 0
       0      .1       0   497.7    .045       0   512.7      .1       0
Bank Sta=497.7,512.7
XS Rating Curve= 0 ,0
Exp/Cntr=0.3,0.1

Type RM Length L Ch R = 1 ,33859.4 ,804,804.5,805
XS GIS Cut Line= 2
     2074020.216      363104.672     2073712.659      364460.278
#Sta/Elev= 30
       0 2689.31    30.2 2685.74    90.7 2674.45   120.9 2668.06   161.2 2658.65
   181.3 2653.15   221.6 2637.58   241.8 2631.96     272 2625.83   372.7 2603.42
   453.3 2582.78   483.5 2577.04   492.3 2576.45   493.6 2576.36   507.3 2576.75
   705.1 2587.92   735.3 2590.13   765.5 2593.72   866.3 2611.74   916.6 2622.56
   946.8 2630.17   997.2 2641.67  1128.2 2680.46  1188.6 2700.69  1228.9 2717.61
  1279.3 2740.57  1289.3 2744.57  1299.4 2747.49  1319.6 2750.48  1390.1 2756.84
#Mann= 3 , 0 , 0
       0      .1       0   492.3    .045       0   507.3      .1       0
Bank Sta=492.3,507.3
XS Rating Curve= 0 ,0
Exp/Cntr=0.3,0.1

Type RM Length L Ch R = 1 ,33054.9 ,648,659.9,671.8
XS GIS Cut Line= 2
     2073274.166      362889.465     2072976.468      364201.616
#Sta/Elev= 30
       0 2693.49    80.3 2680.43   180.7 2667.32   230.9 2657.87   261.1  2650.7
   281.2 2644.52   311.3 2632.02   341.4 2617.56   361.5 2608.74   381.6 2601.42
   401.6 2595.22   471.9 2577.57     502 2571.21   552.3  2567.5   572.3 2567.04
   655.2 2567.29   670.2 2567.28   692.8 2568.18   763.1 2578.44   843.4 2591.52
   903.7 2598.96   933.8  2603.6   953.9 2607.65     974 2613.02  1034.2 2632.79
  1054.3 2638.69  1094.5 2647.98  1114.6  2651.5  1275.2  2672.3  1345.5 2685.58
#Mann= 3 , 0 , 0
       0      .1       0   655.2    .045       0   670.2      .1       0
Bank Sta=655.2,670.2
XS Rating Curve= 0 ,0
Exp/Cntr=0.3,0.1

Type RM Length L Ch R = 1 ,32395   ,742.6,753.9,765.2
XS GIS Cut Line= 2
        2073093.      362766.889     2072174.168      363715.362
#Sta/Elev= 30
       0 2691.23    30.2 2685.63    60.5  2680.8   100.8 2676.15     121 2671.98
   181.4  2655.2   211.7 2647.97   342.7 2614.95   383.1 2604.09   403.2 2597.52
   463.7 2575.08   473.8 2571.58   483.9    2569   544.4 2562.54     625 2556.39
   786.3 2553.36   813.9 2552.44   816.5 2552.32   826.6 2552.72   828.9 2553.37
   836.7 2555.59   856.8 2566.14   887.1  2579.3   897.2 2582.76   907.2 2584.99
     998  2596.6  1088.7 2613.27  1169.3 2625.51  1229.8  2635.8  1320.6 2653.23
#Mann= 3 , 0 , 0
       0      .1       0   813.9    .045       0   828.9      .1       0
Bank Sta=813.9,828.9
XS Rating Curve= 0 ,0
Exp/Cntr=0.3,0.1

Type RM Length L Ch R = 1 ,31641.1 ,1041.3,1043.4,1045.4
XS GIS Cut Line= 2
     2072985.117      362445.039      2071648.21      362860.652
#Sta/Elev= 30
       0 2686.64    20.1 2684.09   191.4 2651.58   211.5 2647.14   302.2  2624.7
   342.4 2616.42   372.7 2612.18     413 2609.35     423 2608.11   433.1 2605.68
   473.4 2590.09   543.9 2565.94   574.1 2555.95   584.2 2552.98   594.2 2550.85
   634.5 2545.62   654.7 2543.85   832.5 2539.85     846 2539.67   847.5 2539.76
   956.8 2549.23   987.1 2550.37  1007.2  2552.4  1017.3 2554.52  1087.8 2573.33
  1107.9 2577.62  1158.3 2592.86  1188.5 2600.52  1359.7 2636.82    1400  2646.3
#Mann= 3 , 0 , 0
       0      .1       0   832.5    .045       0   847.5      .1       0
Bank Sta=832.5,847.5
XS Rating Curve= 0 ,0
Exp/Cntr=0.3,0.1

Type RM Length L Ch R = 1 ,30597.7 ,504.9,502.1,499.3
XS GIS Cut Line= 2
     2072669.272      361502.769     2071327.061      361916.667
#Sta/Elev= 30
       0 2683.27    50.2 2668.64   110.4 2653.79   120.4 2649.77   140.5 2638.62
   200.6 2601.15   230.8 2583.37   260.8 2569.26     291 2552.86     311 2543.01
   331.1 2535.18   351.1 2529.57   361.2 2527.98   381.2 2526.75   461.5 2526.31
     602 2522.74   662.2 2522.91   728.9 2520.46   732.4 2520.41   743.9 2520.73
   782.6 2522.42   812.6 2524.88   852.8 2529.69     923 2539.41     933 2541.53
   963.1 2551.29  1043.4 2571.93  1073.5 2578.88  1183.9 2599.01  1404.6  2641.7
#Mann= 3 , 0 , 0
       0      .1       0   728.9    .045       0   743.9      .1       0
Bank Sta=728.9,743.9
XS Rating Curve= 0 ,0
Exp/Cntr=0.3,0.1

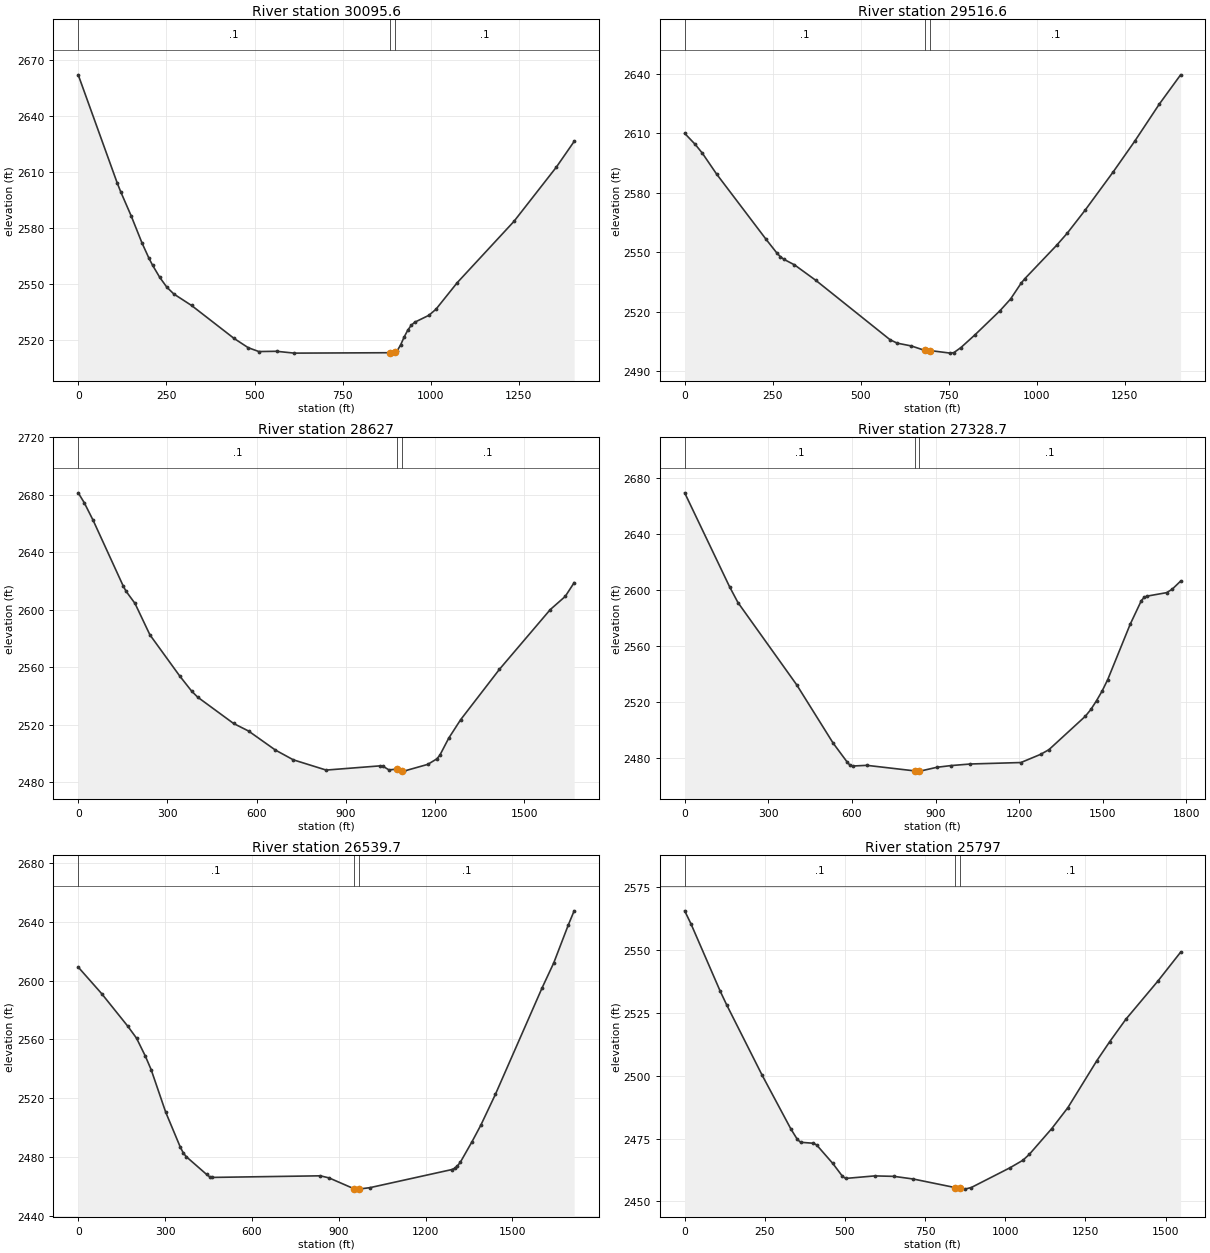
Type RM Length L Ch R = 1 ,30095.6 ,615.7,579,611.3
XS GIS Cut Line= 2
     2072527.142      361078.747     2071183.008      361493.238
#Sta/Elev= 30
       0 2662.29   110.5 2604.31   120.6  2599.5   150.7 2586.38   180.8 2572.12
   200.9 2563.76     211 2560.09   231.1 2553.65   251.2 2548.37   271.3 2544.67
   321.5 2538.52   442.1 2520.83   482.3 2515.85   512.4  2513.8   562.6 2513.93
   612.9 2512.95   884.2 2513.17   899.2 2513.64   904.2 2514.09   914.3  2517.3
   924.3 2521.53   934.4 2525.17   944.4 2527.86   954.5 2529.54   994.7 2533.25
  1014.8 2536.53    1075 2550.76  1235.8 2583.63  1356.4 2612.83  1406.6 2626.56
#Mann= 3 , 0 , 0
       0      .1       0   884.2    .045       0   899.2      .1       0
Bank Sta=884.2,899.2
XS Rating Curve= 0 ,0
Exp/Cntr=0.3,0.1

Type RM Length L Ch R = 1 ,29516.6 ,882.4,889.5,896.6
XS GIS Cut Line= 2
     2072355.933      360567.974     2071009.482      360983.179
#Sta/Elev= 30
       0 2610.05    30.2 2604.42    50.3 2600.01    90.6 2589.52   231.5 2556.49
   261.7 2549.68   271.7  2547.8   281.8 2546.46     312 2543.65   372.4 2535.86
   583.7 2505.83   603.9 2504.12   644.1 2502.71   681.8 2500.48   696.8 2500.39
   754.8 2499.09   764.9 2499.36     785 2501.93   825.3 2508.42   895.7 2520.48
   925.9 2526.42   956.1 2534.46   966.2 2536.64  1056.8 2553.54    1087 2559.66
  1137.3 2571.17  1217.8 2590.67  1278.2 2605.97  1348.6 2624.85    1409 2639.59
#Mann= 3 , 0 , 0
       0      .1       0   681.8    .045       0   696.8      .1       0
Bank Sta=681.8,696.8
XS Rating Curve= 0 ,0
Exp/Cntr=0.3,0.1

Type RM Length L Ch R = 1 ,28627   ,1290.3,1298.3,1306.4
XS GIS Cut Line= 2
     2072435.832      359931.323       2070769.2      360012.623
#Sta/Elev= 30
       0 2681.46    20.1 2674.67    50.3  2662.3   150.8 2616.94   160.8 2613.06
     191 2604.56   241.2  2582.7   341.8 2553.99     382 2543.46   402.1 2539.33
   522.7 2521.05     573  2515.8   663.4 2502.56   723.7 2495.76   834.3 2488.63
  1015.2 2491.56  1025.3  2491.3  1045.4 2488.76  1073.9 2489.33  1088.9 2488.16
  1095.7  2487.9  1176.1  2492.6  1206.2 2496.38  1216.3  2498.8  1246.4 2510.76
  1286.6 2523.65  1417.3 2558.73  1588.2 2600.25  1638.5 2609.39  1668.6 2618.98
#Mann= 3 , 0 , 0
       0      .1       0  1073.9    .045       0  1088.9      .1       0
Bank Sta=1073.9,1088.9
XS Rating Curve= 0 ,0
Exp/Cntr=0.3,0.1

Type RM Length L Ch R = 1 ,27328.7 ,814.9,788.9,801.5
XS GIS Cut Line= 2
     2072607.875      359331.002     2070936.674      358720.681
#Sta/Elev= 30
       0 2669.43   160.8 2602.55     191  2591.2   402.1 2532.42   532.7 2490.88
     583 2477.38     593 2475.14   603.1 2474.57   653.4 2475.06   824.7 2471.11
   839.7 2470.95   844.4 2470.93   904.7 2473.67   954.9 2474.88  1025.3 2476.02
  1206.2 2477.06  1276.6 2482.87  1306.7 2486.23  1437.4 2510.08  1457.5 2514.99
  1477.6 2521.21  1497.7  2528.1  1517.8 2536.27  1598.2 2575.66  1638.4 2592.57
  1648.5 2594.87  1658.5 2595.74  1728.9 2598.23    1749 2600.68  1779.2 2606.47
#Mann= 3 , 0 , 0
       0      .1       0   824.7    .045       0   839.7      .1       0
Bank Sta=824.7,839.7
XS Rating Curve= 0 ,0
Exp/Cntr=0.3,0.1

Type RM Length L Ch R = 1 ,26539.7 ,747.9,742.7,737.4
XS GIS Cut Line= 2
     2072810.525      358623.885     2071193.752      358057.623
#Sta/Elev= 30
       0 2609.18    80.6  2591.2   171.3 2568.93   201.5 2560.79   231.8 2548.63
   251.9  2539.4   302.3  2510.4   352.7 2486.62   362.8  2482.8   372.8 2480.23
   443.4 2468.09   453.5 2466.56   463.5 2466.04   836.4 2467.13   866.6  2465.7
   953.4 2458.26   967.4 2458.07   968.4 2458.08  1007.7 2459.07  1289.8 2471.35
  1299.9 2472.16    1310 2473.87  1320.1 2476.43  1360.4 2490.39  1390.6 2501.55
    1441 2522.55  1602.2 2594.97  1642.5 2611.98  1692.9 2637.85  1713.1 2647.47
#Mann= 3 , 0 , 0
       0      .1       0   953.4    .045       0   968.4      .1       0
Bank Sta=953.4,968.4
XS Rating Curve= 0 ,0
Exp/Cntr=0.3,0.1

Type RM Length L Ch R = 1 ,25797   ,826,822.7,819.4
XS GIS Cut Line= 2
     2072972.925      357696.979     2071435.411      357524.736
#Sta/Elev= 30
       0 2565.63    20.1 2560.32   110.5 2533.76   130.6 2528.33   241.1 2500.37
   331.5  2478.8   351.6 2474.68   361.7 2473.56   401.8 2473.16   411.9 2472.46
   462.1 2465.13   492.3 2460.01   502.3 2459.18   592.7 2460.18     653    2460
   713.3 2458.94     844 2455.53     859 2455.19     874 2454.92   894.1 2455.56
  1014.7 2463.41  1054.9 2466.39    1075 2468.74  1145.3 2479.03  1195.5 2487.36
  1285.9 2506.05  1326.1 2513.62  1376.3  2522.5  1476.8 2537.78  1547.1 2549.18
#Mann= 3 , 0 , 0
       0      .1       0     844    .045       0     859      .1       0
Bank Sta=844,859
XS Rating Curve= 0 ,0
Exp/Cntr=0.3,0.1