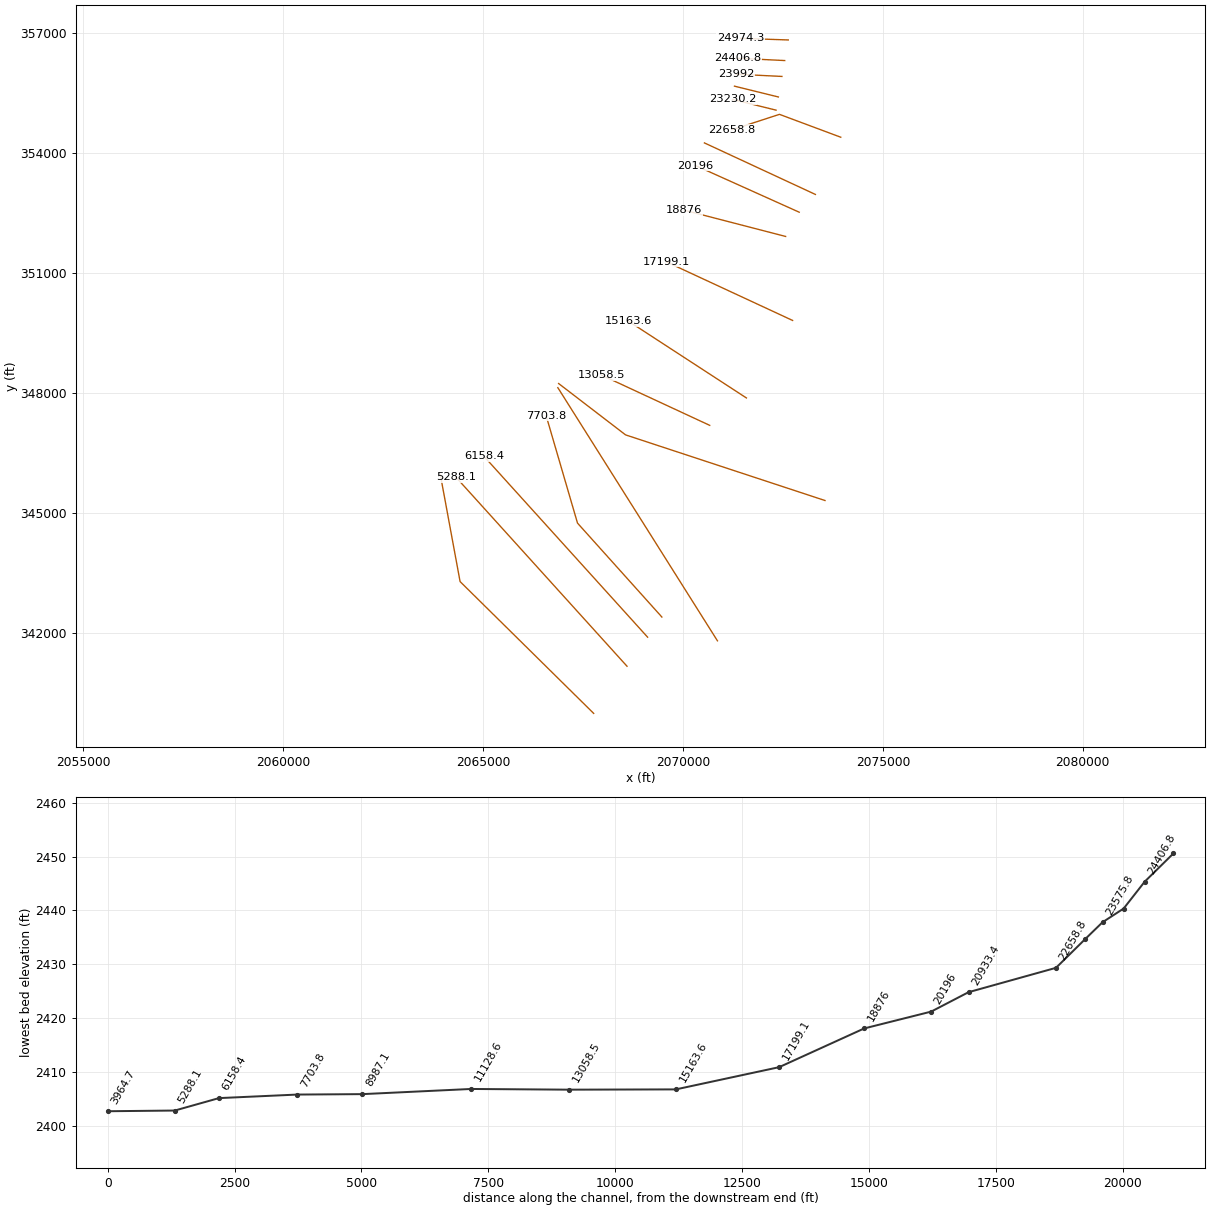
HEC-RAS study LittleClCk.prj: LittleClCk

--- LittleClCk.g01 (geometry) --- (continued)

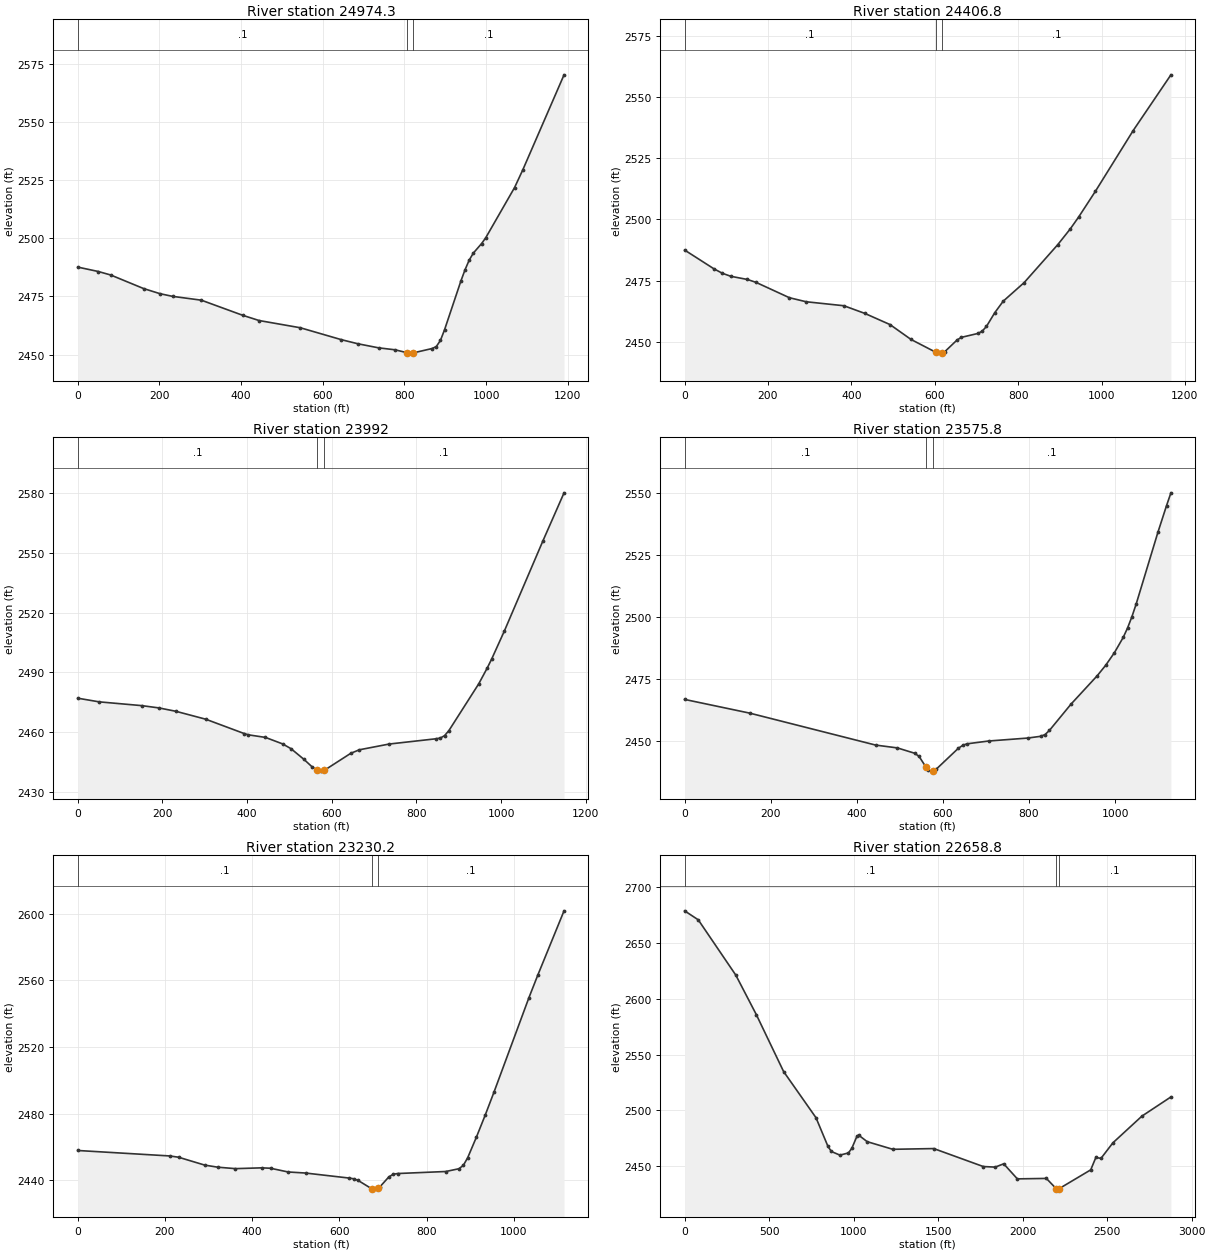
Type RM Length L Ch R = 1 ,24974.3 ,570.1,567.1,564.2
XS GIS Cut Line= 2
     2072635.918      356829.857     2071445.888      356870.426
#Sta/Elev= 30
       0 2487.65    50.4 2485.75    80.7 2484.25   161.4  2478.4   201.8 2476.18
   232.1 2475.05   302.7  2473.4   403.6 2466.91     444 2464.64   544.9 2461.53
   645.8 2456.38   686.2 2454.62   736.6 2452.88     777 2452.03   806.1 2450.79
   817.4  2450.6   821.1 2450.68   867.8 2452.59   877.9 2453.43     888 2456.05
   898.1 2460.65   938.4 2481.79   948.5 2486.59   958.6 2490.71   968.7  2493.7
   988.9  2497.8     999 2500.29  1069.6 2521.91  1089.8 2529.56  1190.7 2570.45
#Mann= 3 , 0 , 0
       0      .1       0   806.1    .045       0   821.1      .1       0
Bank Sta=806.1,821.1
XS Rating Curve= 0 ,0
Exp/Cntr=0.3,0.1

Type RM Length L Ch R = 1 ,24406.8 ,411.4,414.5,417.6
XS GIS Cut Line= 2
     2072546.245      356315.216     2071381.164      356372.049
#Sta/Elev= 30
       0 2487.48    70.4  2479.8    90.5 2477.99   110.6 2476.76   150.8 2475.44
     171 2474.29   251.4 2467.99   291.6 2466.34   382.1 2464.71   432.4 2461.57
   492.7 2457.01     543 2450.94   602.4  2445.7   613.4 2445.34   617.4 2445.54
   623.5 2445.84   653.6 2450.72   663.7 2451.78   703.9  2453.4     714 2454.35
     724 2456.25   744.1  2461.9   764.2 2466.57   814.5 2474.18     895 2489.67
   925.1 2496.13   945.2 2500.99   985.5 2511.54    1076 2536.34  1166.5 2559.11
#Mann= 3 , 0 , 0
       0      .1       0   602.4    .045       0   617.4      .1       0
Bank Sta=602.4,617.4
XS Rating Curve= 0 ,0
Exp/Cntr=0.3,0.1

Type RM Length L Ch R = 1 ,23992   ,420.6,416.3,412
XS GIS Cut Line= 2
     2072477.054      355918.115     2071329.482      355974.094
#Sta/Elev= 30
       0 2476.97    50.4 2475.14   151.2 2473.24   191.5  2472.1   231.8  2470.4
   302.4 2466.42   393.1 2459.23   403.1 2458.58   443.4 2457.28   483.8 2454.04
   503.9 2451.62   534.2  2446.3   554.3 2442.38   565.9 2440.73   574.5 2440.35
   580.9 2440.78   584.6 2441.03     645 2449.29   665.2 2451.06   735.7 2453.95
   846.6  2456.6   856.7 2456.97   866.7 2458.18   876.8 2460.68   947.4  2484.2
   967.5 2492.16   977.6 2496.49  1007.8 2510.66  1098.5 2555.72  1148.9 2580.09
#Mann= 3 , 0 , 0
       0      .1       0   565.9    .045       0   580.9      .1       0
Bank Sta=565.9,580.9
XS Rating Curve= 0 ,0
Exp/Cntr=0.3,0.1

Type RM Length L Ch R = 1 ,23575.8 ,345,345,345.1
XS GIS Cut Line= 2
      2072387.61      355404.785     2071290.611      355674.786
#Sta/Elev= 30
       0 2466.71   151.3 2461.18   443.8  2448.3   494.3 2447.16   534.6    2445
   544.7 2443.72   561.2 2439.28   564.9 2438.38     575  2437.8   576.2  2437.9
     585 2438.66   635.5 2446.95   645.6 2448.15   655.6  2448.8   706.1 2449.94
   796.9 2451.13   827.1 2451.84   837.2 2452.53   847.3 2454.18   897.7 2464.83
   958.3 2476.22   978.4 2480.53   998.6  2485.6  1018.8 2491.69  1028.9 2495.48
    1039 2500.02    1049 2505.18  1099.5  2534.1  1119.6 2544.89  1129.7    2550
#Mann= 3 , 0 , 0
       0      .1       0   561.2    .045       0   576.2      .1       0
Bank Sta=561.2,576.2
XS Rating Curve= 0 ,0
Exp/Cntr=0.3,0.1

Type RM Length L Ch R = 1 ,23230.2 ,562,571.5,581
XS GIS Cut Line= 2
      2072330.22      355075.419     2071247.473      355342.628
#Sta/Elev= 30
       0 2457.84     211 2454.56   231.1  2453.8   291.4 2449.05   321.5  2447.8
   361.7 2446.94     422 2447.42   442.1 2447.18   482.3 2444.94   522.4  2444.3
   622.9 2441.27     633 2440.83     643 2439.86   673.8 2434.91   683.2 2434.64
   688.8 2435.46   693.2  2436.1   713.4 2441.97   723.4 2443.56   733.4    2444
     844 2445.22   874.1 2446.88   884.2  2448.9   894.2 2453.46   914.3  2465.9
   934.4 2479.06   954.5 2492.84  1034.8 2549.68    1055 2563.13  1115.2 2601.73
#Mann= 3 , 0 , 0
       0      .1       0   673.8    .045       0   688.8      .1       0
Bank Sta=673.8,688.8
XS Rating Curve= 0 ,0
Exp/Cntr=0.3,0.1

Type RM Length L Ch R = 1 ,22658.8 ,1739.5,1723.7,1707.7
XS GIS Cut Line= 3
     2073947.799      354398.603     2072415.445      354970.222
      2071234.79      354585.321
#Sta/Elev= 30
       0 2679.03    80.8 2670.95   302.9 2621.35     424    2586   585.6 2534.85
   777.4 2493.39     848 2467.74   868.2 2463.11   918.7 2459.84   969.2 2461.79
   989.4 2465.99  1019.7 2476.81  1029.8 2477.76  1080.2 2471.91  1231.7 2465.06
    1474 2465.72  1766.8 2449.61  1837.4 2449.07  1887.9 2452.04  1968.7 2438.53
  2140.3 2438.94  2197.7 2429.89    2211 2429.33  2212.7 2429.47  2402.8 2446.62
  2433.1 2457.73  2463.4 2456.91    2534 2470.88  2705.7 2494.84  2877.3 2512.05
#Mann= 3 , 0 , 0
       0      .1       0  2197.7    .045       0  2212.7      .1       0
Bank Sta=2197.7,2212.7
XS Rating Curve= 0 ,0
Exp/Cntr=0.3,0.1

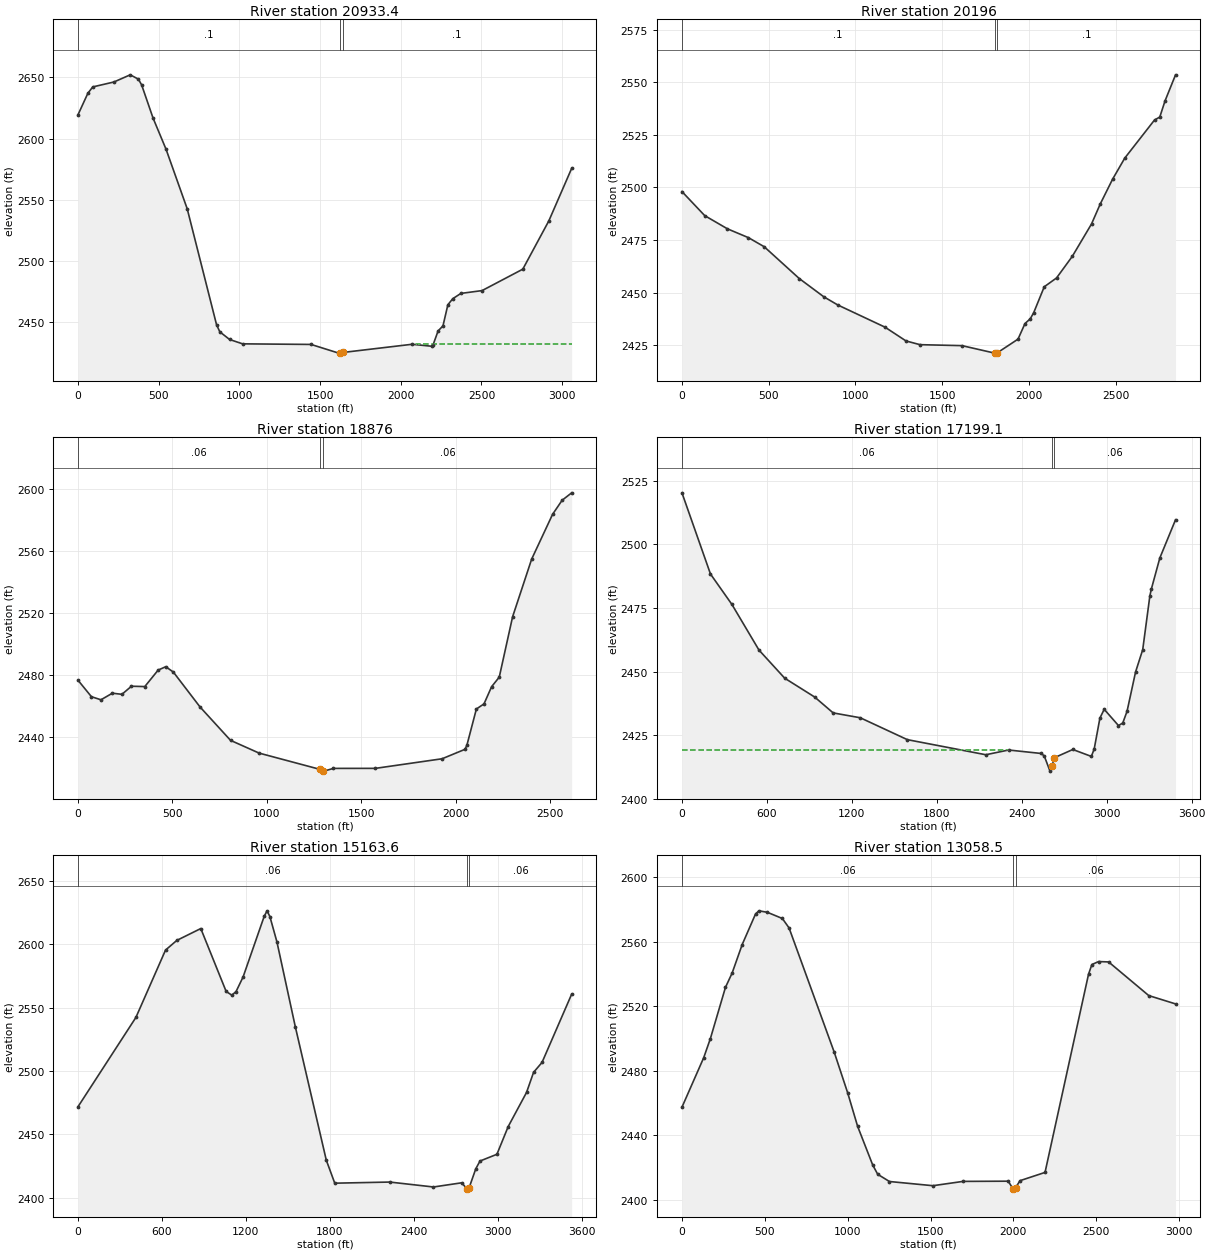
Type RM Length L Ch R = 1 ,20933.4 ,735.8,736.6,737.4
XS GIS Cut Line= 2
     2073313.848      352968.286     2070539.185      354256.105
#Sta/Elev= 30
       0 2619.58    60.6 2636.99    90.9 2642.17   222.1 2646.19   323.1 2652.04
   373.5 2648.52   393.7 2643.85   464.4  2616.8   545.2 2591.24   676.4 2542.58
   858.1 2447.99   878.3  2442.2   938.9 2435.94  1019.6 2432.38  1443.7  2431.9
  1615.3  2424.8  1625.5 2424.95  1640.5 2425.33  2069.6 2432.02  2190.7 2430.43
  2200.8 2431.81  2231.1 2442.92  2261.4 2447.05  2291.7 2464.27    2322 2469.24
  2372.5 2473.56  2503.7 2475.86  2756.1 2493.35  2917.6 2532.82    3059 2575.67
#Mann= 3 , 0 , 0
       0      .1       0  1625.5    .045       0  1640.5      .1       0
#XS Ineff= 2 , 0
                         2092.23         2432.07
Permanent Ineff=
       F       F
Bank Sta=1625.5,1640.5
XS Rating Curve= 0 ,0
Exp/Cntr=0.3,0.1

Type RM Length L Ch R = 1 ,20196   ,1314,1320,1324.6
XS GIS Cut Line= 2
     2072909.299      352523.852     2070314.254      353690.894
#Sta/Elev= 30
       0 2497.98   131.2 2486.55   262.3 2480.27   383.4 2476.07   474.2 2471.76
     676 2456.66   817.3 2447.99     898 2444.09  1170.4 2433.54  1291.5 2426.98
  1372.2 2425.21  1614.4 2424.75  1801.9 2421.21  1806.1 2421.19  1816.9 2421.29
  1937.3 2427.84  1977.6 2435.26  2007.9  2437.5  2028.1 2440.48  2088.6 2452.73
  2159.3 2456.91  2250.1 2467.17  2361.1 2482.59  2411.5  2492.1  2482.2 2503.81
  2552.8  2513.9  2724.3 2532.01  2754.6  2533.4  2784.8 2541.07  2845.4 2553.47
#Mann= 3 , 0 , 0
       0      .1       0  1801.9    .045       0  1816.9      .1       0
Bank Sta=1801.9,1816.9
XS Rating Curve= 0 ,0
Exp/Cntr=0.3,0.1

Type RM Length L Ch R = 1 ,18876   ,1680.1,1676.7,1672.7
XS GIS Cut Line= 2
     2072570.223      351917.798     2070038.552      352573.483
#Sta/Elev= 30
       0 2476.55    70.7    2466   121.2 2464.02   181.8 2468.27   232.2 2467.53
   282.7 2472.75   353.4 2472.53   424.1 2483.14   464.5 2485.33   504.9 2481.85
   646.2 2459.38   807.8 2437.88   959.2 2429.67  1283.7 2419.13  1298.7 2418.23
  1302.6 2418.06    1353 2419.82  1575.2 2419.84  1928.6 2426.02  2049.8  2432.1
  2059.8 2434.62  2110.3 2458.08  2150.7 2461.38  2191.1 2472.47  2231.5 2478.61
  2302.2 2517.49  2403.2 2554.64  2514.2 2583.52  2564.7 2592.56  2615.2 2597.34
#Mann= 3 , 0 , 0
       0     .06       0  1283.7    .045       0  1298.7     .06       0
Bank Sta=1283.7,1298.7
XS Rating Curve= 0 ,0
Exp/Cntr=0.3,0.1

Type RM Length L Ch R = 1 ,17199.1 ,2037.9,2035.1,2033.1
XS GIS Cut Line= 2
     2072744.627      349817.915     2069582.372      351285.628
#Sta/Elev= 30
       0 2520.23   201.5 2488.32   352.7 2476.38   544.1 2458.43   725.5 2447.39
   937.1 2439.99    1068 2433.74  1259.5 2431.83    1592 2423.23  2146.2  2417.3
  2307.4 2419.16  2539.1 2417.79  2559.3 2416.78  2599.6 2410.86  2614.2 2412.85
  2629.2  2416.1  2760.8 2419.36  2891.8 2416.64  2911.9 2419.59  2952.2 2431.72
  2982.5 2435.15  3083.2 2428.77  3113.5 2429.77  3143.7 2434.35  3204.1 2449.85
  3254.5 2458.59  3304.9  2479.7    3315 2482.32  3375.4 2494.63  3486.3 2509.65
#Mann= 3 , 0 , 0
       0     .06       0  2614.2    .045       0  2629.2     .06       0
#XS Ineff= 2 , 0
         2309.48 2419.16
Permanent Ineff=
       F       F
Bank Sta=2614.2,2629.2
XS Rating Curve= 0 ,0
Exp/Cntr=0.3,0.1

Type RM Length L Ch R = 1 ,15163.6 ,2103,2105.1,2112.2
XS GIS Cut Line= 2
     2071588.494      347880.801     2068631.028      349805.767
#Sta/Elev= 30
       0 2471.85   413.4  2542.2   625.1 2595.32   705.8 2602.96   877.2 2612.31
  1058.6 2562.67    1099 2559.76  1129.2 2562.57  1179.6  2574.1  1330.8 2622.02
    1351 2626.29  1371.2 2621.78  1421.6 2601.77  1552.6 2535.03  1774.5 2429.58
    1835 2411.42  2228.2 2412.31  2540.7 2408.42  2742.4 2411.72  2780.1 2407.02
  2782.7 2406.73  2795.1 2407.62  2843.2 2422.76  2873.4  2428.9  2994.4 2434.22
  3075.1 2456.11  3206.1    2483  3256.5 2498.89    3317 2506.71  3528.8 2560.56
#Mann= 3 , 0 , 0
       0     .06       0  2780.1    .045       0  2795.1     .06       0
Bank Sta=2780.1,2795.1
XS Rating Curve= 0 ,0
Exp/Cntr=0.3,0.1

Type RM Length L Ch R = 1 ,13058.5 ,1935.3,1929.5,1923.8
XS GIS Cut Line= 2
     2070671.191      347195.778     2067969.657      348449.654
#Sta/Elev= 30
       0 2457.42   131.2 2488.07   171.6 2499.94   262.5 2531.63   302.9 2540.55
   363.5 2558.16   444.2 2577.13   464.4 2579.03   514.9 2578.13   605.8 2574.28
   646.2 2568.45   918.7 2491.52   999.5 2466.45  1060.1 2445.52    1151 2421.63
  1181.2 2415.86  1251.9  2411.4  1514.4  2408.8  1696.1 2411.47  1968.7  2411.6
  1998.9 2406.68  2013.9 2407.59  2039.4  2411.9  2190.8 2417.03  2453.3 2539.77
  2473.5 2545.77  2513.9 2547.61  2574.5 2547.38  2816.8 2526.54  2978.3 2521.39
#Mann= 3 , 0 , 0
       0     .06       0  1998.9    .045       0  2013.9     .06       0
Bank Sta=1998.9,2013.9
XS Rating Curve= 0 ,0
Exp/Cntr=0.3,0.1

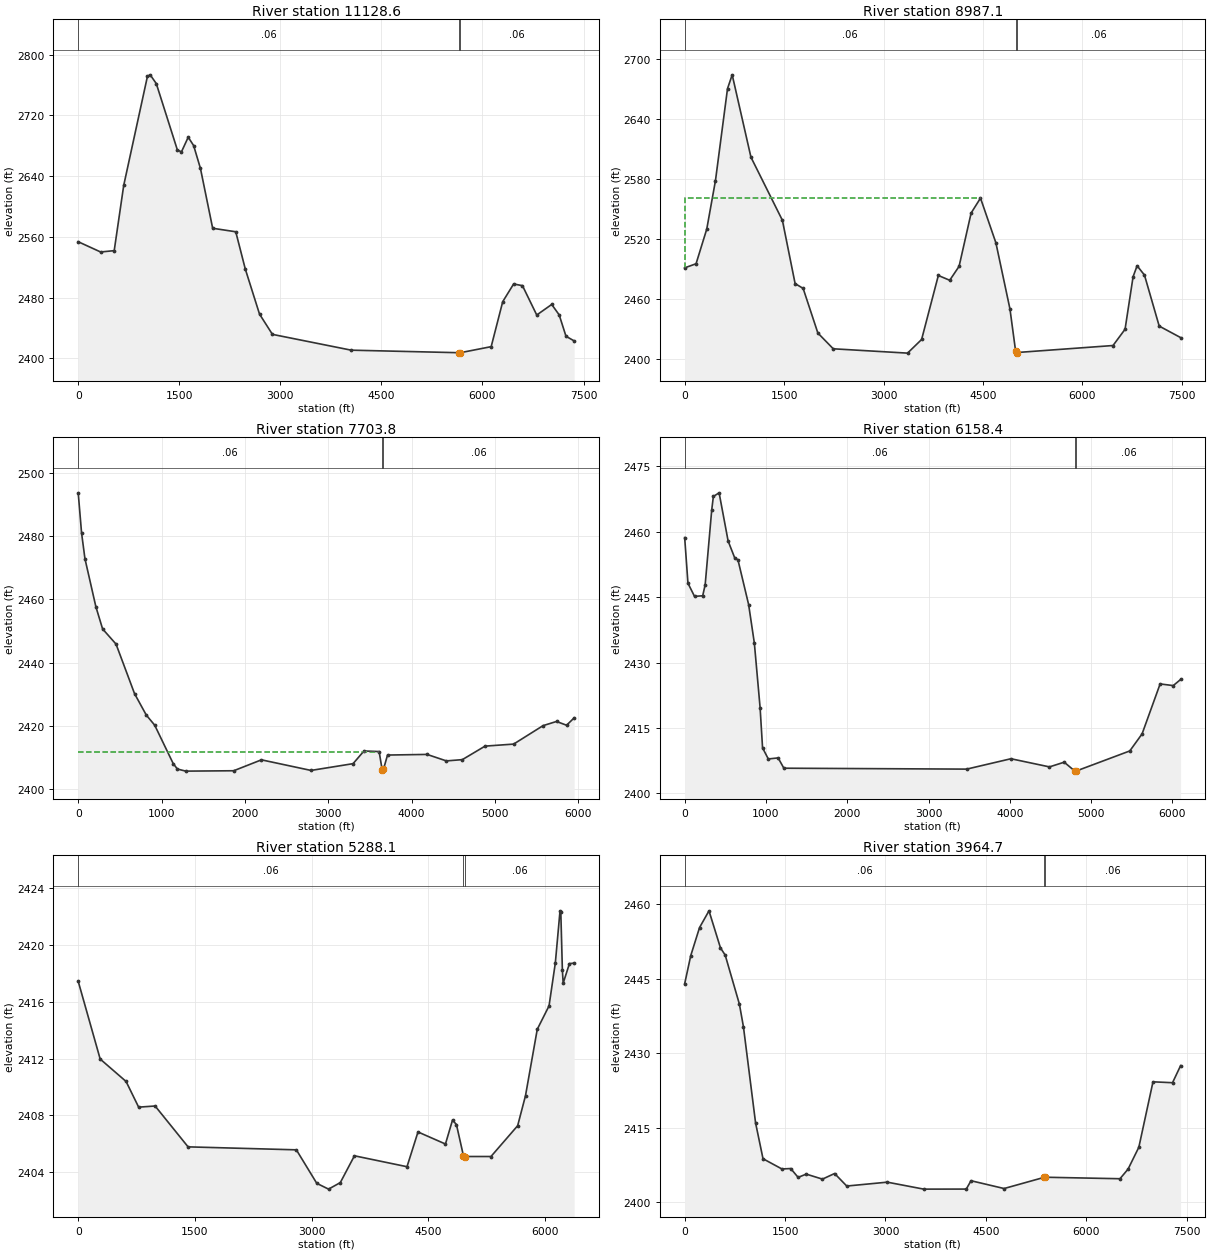
Type RM Length L Ch R = 1 ,11128.6 ,2151.9,2140.5,2123.8
XS GIS Cut Line= 3
      2073554.68      345316.595     2068566.871      346957.747
     2066892.916      348241.654
#Sta/Elev= 30
       0 2553.51   332.6 2540.02   534.2 2541.78   675.3 2627.69    1028 2771.55
  1068.3 2773.34    1159 2761.77  1471.4 2674.48  1531.9 2671.83  1632.7  2691.2
  1713.3 2680.11  1814.1 2650.08  1995.5 2571.26  2338.2 2566.64  2479.3 2517.71
  2690.9  2458.2  2882.4 2431.52  4051.5 2410.71  5654.1 2407.35  5664.7 2406.81
  5669.1 2407.32    6129 2415.34  6300.6 2474.62  6462.1 2497.88  6593.4 2495.67
  6805.3 2457.01  7027.4 2470.92  7138.4 2457.17  7239.4 2429.02  7360.5 2422.92
#Mann= 3 , 0 , 0
       0     .06       0  5654.1    .045       0  5669.1     .06       0
Bank Sta=5654.1,5669.1
XS Rating Curve= 0 ,0
Exp/Cntr=0.3,0.1

Type RM Length L Ch R = 1 ,8987.1  ,1289.5,1283.2,1276.9
XS GIS Cut Line= 2
     2070864.703       341809.41     2066873.513      348138.148
#Sta/Elev= 30
       0 2491.19   171.7  2495.3   333.2 2530.05   464.5 2578.53   646.2 2670.56
   716.9 2684.38   999.6 2601.98  1474.2  2538.8  1666.1 2475.44  1787.2 2470.63
  2009.4 2425.96  2241.6 2410.19  3362.4 2405.85  3574.5 2419.49  3826.9 2483.57
  3998.6 2478.76  4139.9  2492.7  4321.7 2546.07    4463 2561.01  4695.3 2516.24
  4907.3  2450.1  4993.4 2407.56  5008.4 2406.44  6462.3 2413.46  6644.1 2429.76
  6765.2 2482.34  6825.8 2493.27  6936.9 2483.96    7159 2432.92  7482.2 2421.41
#Mann= 3 , 0 , 0
       0     .06       0  4993.4    .045       0  5008.4     .06       0
#XS Ineff= 2 , 0
         4464.13 2560.66
Permanent Ineff=
       F       F
Bank Sta=4993.4,5008.4
XS Rating Curve= 0 ,0
Exp/Cntr=0.3,0.1

Type RM Length L Ch R = 1 ,7703.8  ,1534.6,1545.2,1555.9
XS GIS Cut Line= 3
     2069475.076      342403.788     2067365.353       344752.08
     2066581.957      347434.343
#Sta/Elev= 30
       0  2493.7    40.3 2481.02    80.7  2472.9   211.8 2457.73   292.5  2450.7
   453.8 2445.91   675.7 2430.27   816.9 2423.48   917.8 2420.29  1139.7 2408.17
  1190.1 2406.43    1291 2405.77  1865.8 2405.89  2198.7 2409.34  2793.7 2405.99
    3298 2408.13  3429.2 2412.14  3610.8 2411.95  3647.5 2406.16  3662.5  2406.3
  3711.6 2410.85  4185.8 2411.05  4417.8    2409  4609.4  2409.4  4881.8 2413.67
  5224.8 2414.31  5577.9 2420.14  5739.3 2421.46  5860.3 2420.27  5951.1  2422.6
#Mann= 3 , 0 , 0
       0     .06       0  3647.5    .045       0  3662.5     .06       0
#XS Ineff= 2 , 0
         3609.55 2411.96
Permanent Ineff=
       F       F
Bank Sta=3647.5,3662.5
XS Rating Curve= 0 ,0
Exp/Cntr=0.3,0.1

Type RM Length L Ch R = 1 ,6158.4  ,870.3,870.3,870.3
XS GIS Cut Line= 2
     2069118.443      341900.307      2065025.07      346423.231
#Sta/Elev= 30
       0 2458.65    40.3 2448.19     121 2445.17   221.8 2445.31   252.1 2447.85
   332.7    2465   352.9 2468.08   423.5 2468.91   534.4 2457.86   615.1 2454.01
   655.4 2453.54   786.5  2443.3     857 2434.46   927.6 2419.69   957.9 2410.45
  1028.5  2407.9  1149.5 2408.14    1220 2405.78  3468.6 2405.57    4013 2407.95
  4486.9 2406.08  4668.4 2407.16  4799.5 2405.11  4801.4 2405.11  4816.4 2405.14
  5475.1 2409.74  5626.3 2413.65  5848.1  2425.1  6009.5 2424.72  6100.2 2426.12
#Mann= 3 , 0 , 0
       0     .06       0  4801.4    .045       0  4816.4     .06       0
Bank Sta=4801.4,4816.4
XS Rating Curve= 0 ,0
Exp/Cntr=0.3,0.1

Type RM Length L Ch R = 1 ,5288.1  ,1336.3,1323.3,1310.4
XS GIS Cut Line= 2
     2068603.678      341173.579      2064324.83      345901.442
#Sta/Elev= 30
       0 2417.45   282.5 2411.97   615.5 2410.39   776.9 2408.58   988.8 2408.66
  1412.5 2405.78  2804.9 2405.57  3067.2 2403.21  3218.6  2402.8  3369.9 2403.26
  3551.5 2405.15  4227.5 2404.38  4368.8 2406.83  4721.9 2405.98  4812.7 2407.67
  4863.2 2407.35  4953.6 2405.14  4968.6  2405.1  5307.1  2405.1  5650.2 2407.27
  5751.1 2409.39  5902.4 2414.07  6053.8 2415.72  6134.5 2418.74    6195 2422.42
  6205.1 2422.32  6225.3 2418.23  6235.4 2417.32  6316.1  2418.7  6376.6 2418.73
#Mann= 3 , 0 , 0
       0     .06       0  4953.6    .045       0  4968.6     .06       0
Bank Sta=4953.6,4968.6
XS Rating Curve= 0 ,0
Exp/Cntr=0.3,0.1

Type RM Length L Ch R = 1 ,3964.7  ,3973.7,3964.7,3953
XS GIS Cut Line= 3
     2067769.297      339995.629     2064429.189        343290.6
     2063935.459      345963.552
#Sta/Elev= 30
       0 2443.96    90.8 2449.61     222 2455.24   363.2 2458.61   534.8 2451.16
   605.4 2449.71   817.3 2439.87   877.8 2435.32  1059.4 2415.97  1170.4 2408.78
    1453 2406.72  1584.1 2406.81  1695.1 2405.03  1816.2 2405.69  2058.4 2404.68
    2240 2405.81  2421.6 2403.29    3027 2404.07  3571.8 2402.67  4207.5 2402.68
  4278.1 2404.36  4772.4 2402.79  5372.1 2405.04  5387.1 2405.06  6503.9 2404.76
  6624.7 2406.69  6785.8 2411.09  6997.2 2424.24  7289.2 2424.06    7410  2427.5
#Mann= 3 , 0 , 0
       0     .06       0  5372.1    .045       0  5387.1     .06       0
Bank Sta=5372.1,5387.1
XS Rating Curve= 0 ,0
Exp/Cntr=0.3,0.1

Chan Stop Cuts=-1
Use User Specified Reach Order=0
Composite Channel Slope=5